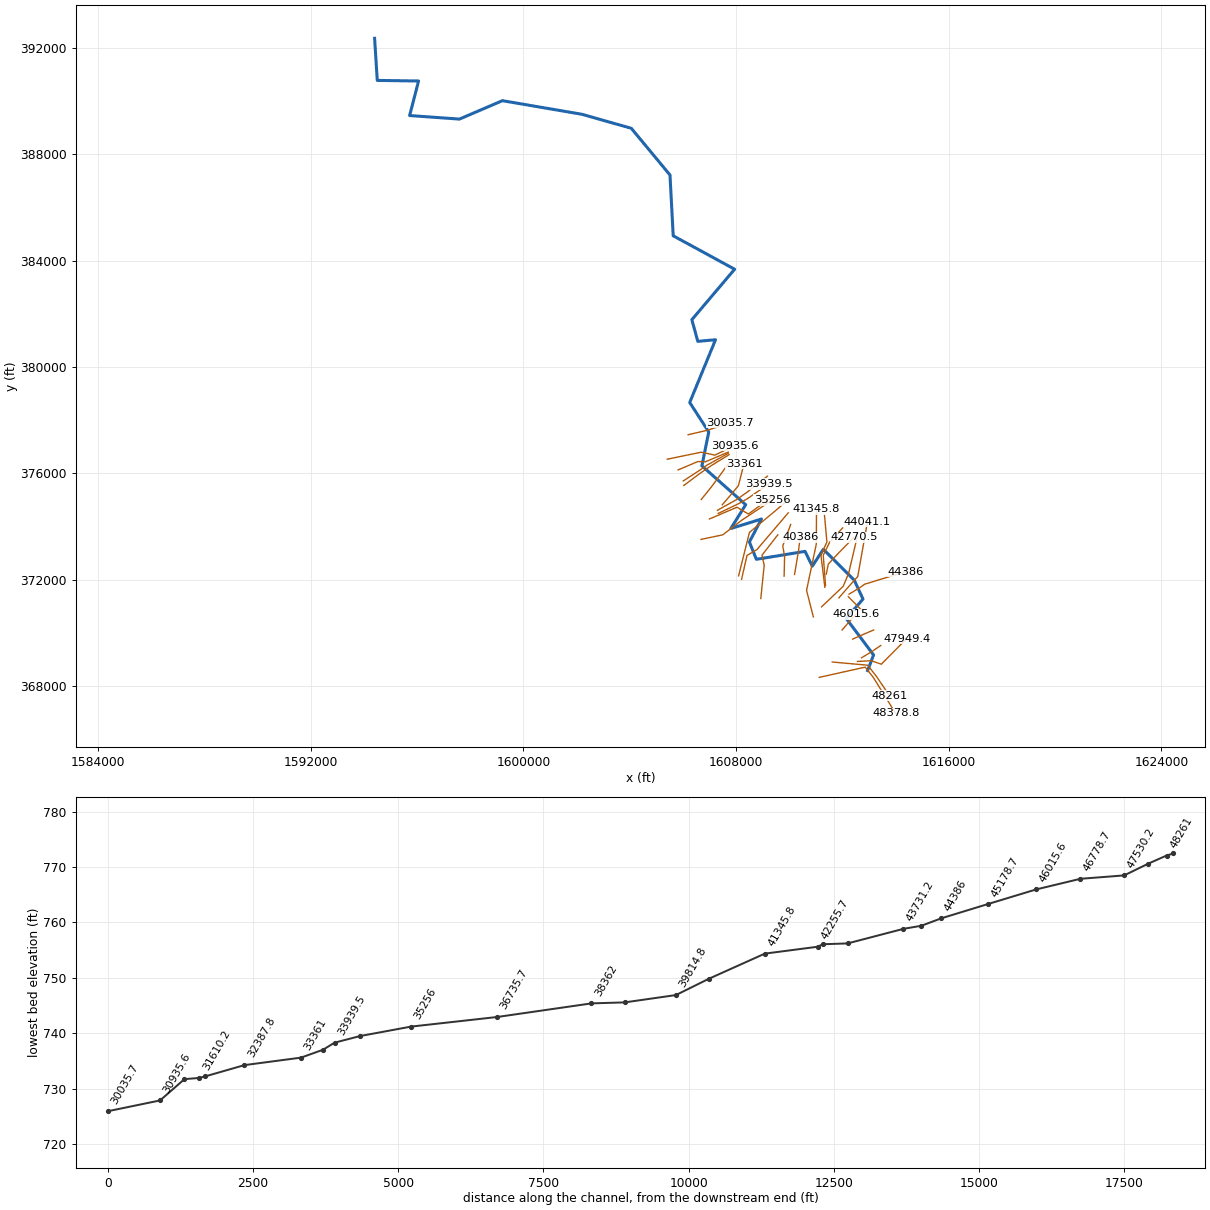
--- KIAHCR.prj (project) ---

Proj Title=KIAHCR
Current Plan=p01
Default Exp/Contr=0,0
English Units
Geom File=g01
Flow File=f01
Plan File=p01
BEGIN DESCRIPTION:
END DESCRIPTION:
DSS Export Rating Curves= 0
DSS Export Rating Curve Sorted= 0
DSS Export Volume Flow Curves= 0
DXF OffsetX= 0
DXF OffsetY= 0
DXF ScaleX= 0
DXF ScaleY= 0

--- KIAHCR.p01 (plan) ---

Plan Title=Floodplain
Program Version=4.00
Geom File=g01
Flow File=f01
K Sum by GR=0
Std Step Tol=0.01
Critical Tol=0.01
Num of Std Step Trials=20
Max Error Tol=0.3
Flow Tol Ratio=0.001
Split Flow NTrial=30
Split Flow Tol=0.02
Split Flow Ratio=0.02
Log Output Level=0
Friction Slope Method=1
Unsteady Friction Slope Method=2
Unsteady Bridges Friction Slope Method=1
Global Log Level=0
CheckData=False
Run HTab=0
Run UNet=0
Run PostProcess=0
UNET Theta=0
UNET Theta Warmup=0
UNET ZTol=0
UNET ZSATol=0
UNET MxIter=0
UNET MaxInSteps=0
UNET DtIC=0
UNET DtMin=0
UNET MaxCRTS=0
UNET WFStab=0
UNET SFStab=0
UNET WFX=0
UNET SFX=0
UNET DSS MLevel=0
UNET DZMax Abort=0
UNET Convert EG Bridges=0
UNET Use Existing IB Tables=0
UNET Froude Limit=0
UNET Froude Power=0
Write IC File=0
Echo Input=False
Echo Output=False
Write Detailed=0

--- KIAHCR.f01 (steady flow) ---

Flow Title=NFF Regression Equation
Program Version=4.00
Number of Profiles= 1
Profile Names=P100yr
River Rch & RM=KIAHCR,Main            ,48378.8
    1466
River Rch & RM=KIAHCR,Main            ,47949.4
    2108
River Rch & RM=KIAHCR,Main            ,44041.1
    2149
River Rch & RM=KIAHCR,Main            ,43731.2
    2456
River Rch & RM=KIAHCR,Main            ,38934.8
    2543
River Rch & RM=KIAHCR,Main            ,35256
    2821
River Rch & RM=KIAHCR,Main            ,22176.8
    3127
River Rch & RM=KIAHCR,Main            ,21829.3
    3692
River Rch & RM=KIAHCR,Main            ,14929.9
    3871
River Rch & RM=KIAHCR,Main            ,14078.9
    4309
Boundary for River Rch & Prof#=KIAHCR,Main            , 1
Up Type= 0
Dn Type= 3
Dn Slope=0.0002
DSS Import GetInterval= 0
DSS Import GetPeak= 0
DSS Import FillOption= 0

--- KIAHCR.g01 (geometry) ---

Geom Title=USGS 10m DEM
Program Version=4.00

River Reach=KIAHCR          ,Main
Reach XY= 30
     1612950.279       368575.15     1613175.167      369161.885
     1612143.232      370539.257     1612777.647      371264.116
     1612445.971      371979.099     1611286.239      373138.276
     1610868.937      372502.059     1610597.583       373059.04
     1608766.067       372760.22     1608502.946      373413.855
     1608956.531      374275.631     1607805.982      373919.303
     1608363.789      374814.317     1606716.337      376277.345
      1606974.62      377551.964     1606258.283       378660.19
      1607229.08      381021.468     1606562.492      380960.598
     1606338.263      381774.981     1607947.972      383674.456
     1605636.889      384931.645     1605515.705      387219.521
      1604059.28       388976.71     1602210.201      389501.902
     1599209.683      390015.237     1597592.888      389323.007
     1595720.518      389455.067     1596057.388      390755.357
     1594502.807       390777.64     1594403.098      392360.665

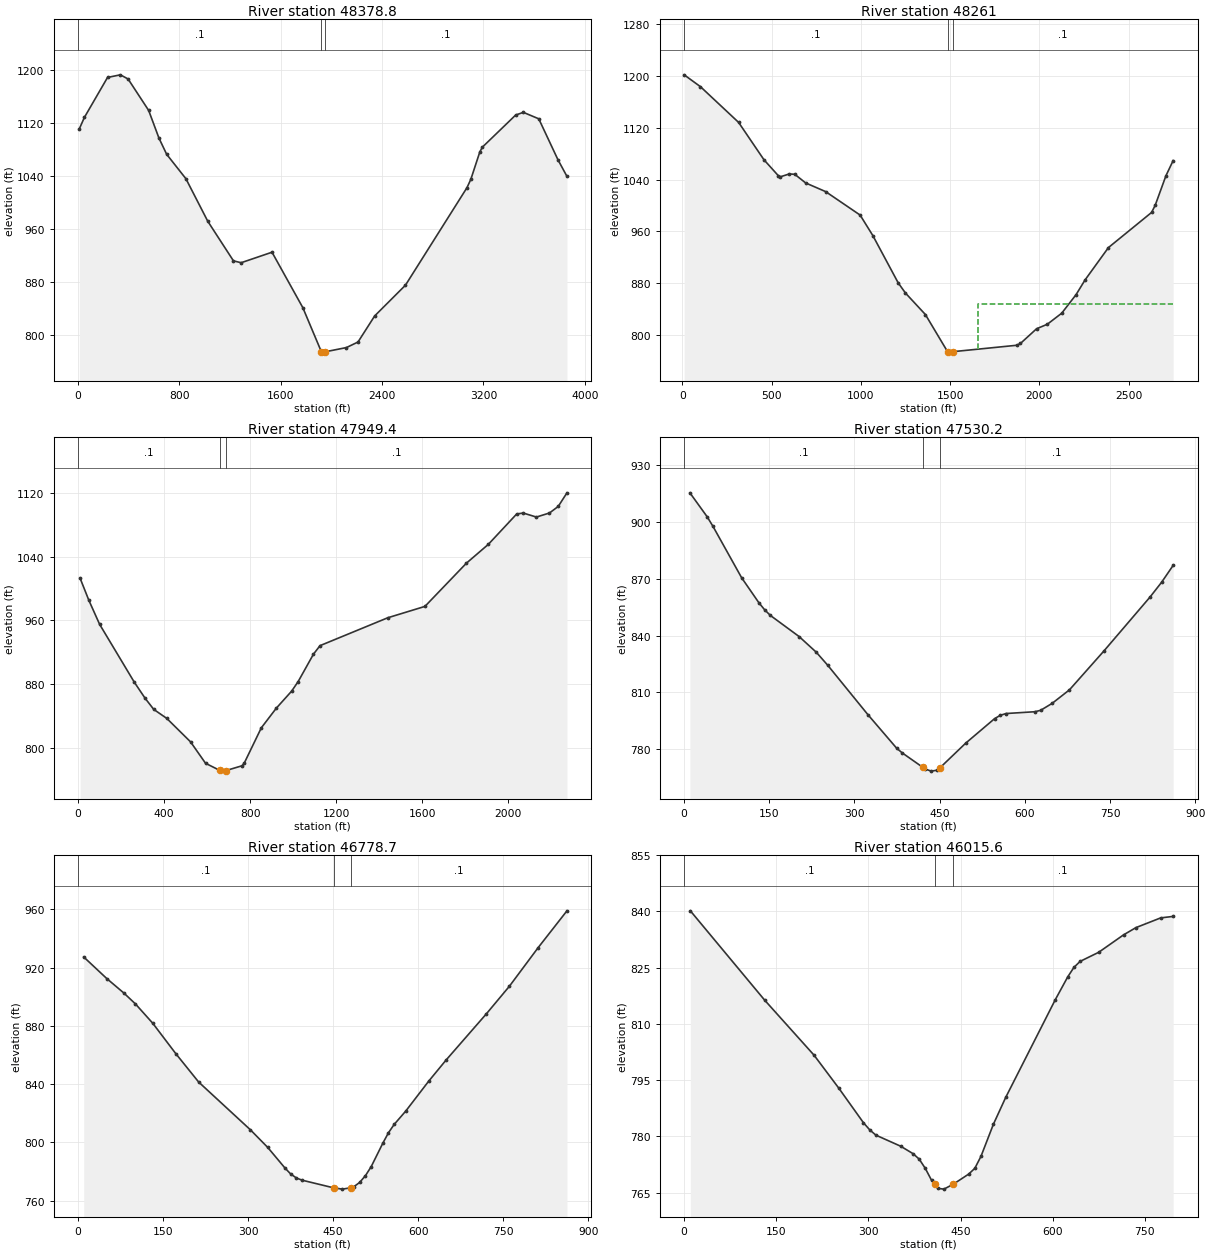
Type RM Length L Ch R = 1 ,48378.8 ,117.9,117.8,117.7
XS GIS Cut Line= 4
     1611129.124       368318.47     1612861.349      368704.046
     1613161.919      368322.238      1614005.02      366964.348
#Sta/Elev= 30
    10.1 1111.55    50.7  1129.1   233.2  1189.5   334.6 1193.45   395.5 1187.12
   557.7 1139.62   638.9 1097.76   699.7 1073.26   851.8 1036.25  1024.2  971.93
    1227     912  1287.9  909.22  1531.2   925.1  1774.6  841.13  1921.6   774.1
  1936.6  772.44  1951.6  774.47  2118.8  780.87  2209.9  789.26  2341.5  828.72
  2584.3   875.2  3069.8 1022.73  3100.2 1035.33    3171  1076.7  3191.2 1084.01
  3454.2 1132.64  3514.9 1136.67  3636.3 1126.93  3788.1 1064.86  3858.9  1039.8
#Mann= 3 , 0 , 0
       0      .1       0  1921.6    .045       0  1951.6      .1       0
Bank Sta=1921.6,1951.6
XS Rating Curve= 0 ,0
Exp/Cntr=0.3,0.1

Type RM Length L Ch R = 1 ,48261   ,294.3,311.7,329
XS GIS Cut Line= 4
     1611619.008       368896.56     1612955.152       368776.58
     1613282.371      368356.649     1613773.199      367631.313
#Sta/Elev= 30
    10.2 1201.72   101.6 1183.39   315.1 1128.33   457.3 1070.58   538.6 1045.72
   548.8 1044.25   599.6 1048.72   630.1 1048.11   691.1 1034.77   802.9 1021.42
     996   985.2  1067.1  953.63  1209.4  880.51  1250.1  864.81  1361.6  831.68
  1487.2  773.71  1502.2  772.06  1517.2  774.34  1873.9   784.2    1894  786.93
  1984.6  809.66    2045  816.66  2125.6  833.73  2206.1  862.43  2256.4  885.12
  2387.3  935.03  2628.9  989.24    2649 1000.14  2709.4  1045.9  2749.7  1069.3
#Mann= 3 , 0 , 0
    10.2      .1       0  1487.2    .045       0  1517.2      .1       0
#XS Ineff= 2 , 0
                          1655.1          848.36
Permanent Ineff=
       F       F
Bank Sta=1487.2,1517.2
XS Rating Curve= 0 ,0
Exp/Cntr=0.3,0.1

Type RM Length L Ch R = 1 ,47949.4 ,393,419.2,446.7
XS GIS Cut Line= 4
     1612567.943      368918.375     1613080.586      368945.643
     1613467.795      368814.755     1614417.705      369775.763
#Sta/Elev= 30
    10.1 1012.94    50.3  985.52   100.7  955.08   261.7  882.46     312  862.23
   352.3   848.2   412.7  836.93   523.3  807.42   593.1  780.46   657.9  771.71
   672.9  770.61   687.9  771.31   762.6  777.34   772.6   780.5   852.3  825.06
   922.1  849.77   993.2  871.15  1023.7  883.24  1094.8   917.7  1125.3  928.37
  1440.2  963.42    1613   977.7    1806 1032.09  1907.6 1055.66  2039.7 1093.93
  2070.2 1095.07  2131.1 1090.03  2192.1 1095.15  2232.7 1103.39  2273.3 1120.49
#Mann= 3 , 0 , 0
       0      .1       0   657.9    .045       0   687.9      .1       0
Bank Sta=657.9,687.9
XS Rating Curve= 0 ,0
Exp/Cntr=0.3,0.1

Type RM Length L Ch R = 1 ,47530.2 ,755,751.5,746.2
XS GIS Cut Line= 3
     1612720.645      369054.716       1613102.4      369283.769
      1613445.98      369518.276
#Sta/Elev= 30
    10.1  915.31    40.5  902.68    50.6   897.7   101.2  870.51   131.5  857.36
   141.7  853.62   151.8  850.63   202.4  839.49   232.7  831.21     253  824.28
   323.8   798.2   374.4  780.51   384.5     778   420.1  770.52     425  769.52
   435.1  768.47   445.2  768.94   450.1   770.1   495.9  783.24   546.7  796.15
   556.8  797.92     567  798.86   617.7  799.81   627.8  800.55   648.1  804.22
   678.6  811.36   739.4   831.9   820.6  860.35   840.9  868.12   861.2  877.01
#Mann= 3 , 0 , 0
       0      .1       0   420.1    .045       0   450.1      .1       0
Bank Sta=420.1,450.1
XS Rating Curve= 0 ,0
Exp/Cntr=0.3,0.1

Type RM Length L Ch R = 1 ,46778.7 ,749.9,763.1,776.7
XS GIS Cut Line= 3
     1612387.972      369758.237     1612814.412      369946.719
     1613178.751      370101.816
#Sta/Elev= 30
    10.1  927.29    50.7  912.49    81.1  902.46   101.4  895.01   131.8  881.79
   172.3  860.99   212.8  841.39   304.1  808.57   334.5  796.53   364.9  782.39
     375  778.28   385.2  775.49   395.3  773.99   451.2   768.7   466.2  767.86
   481.2   768.8   486.5  769.53   496.7  772.48   506.9  777.13     517   783.3
   537.3  799.24   547.5   806.6   557.6  812.34   577.9  821.44   618.5  842.05
     649  856.48   720.1  888.24   760.7  907.19   811.4   933.7   862.2  958.98
#Mann= 3 , 0 , 0
       0      .1       0   451.2    .045       0   481.2      .1       0
Bank Sta=451.2,481.2
XS Rating Curve= 0 ,0
Exp/Cntr=0.3,0.1

Type RM Length L Ch R = 1 ,46015.6 ,888.6,836.9,785.2
XS GIS Cut Line= 3
     1611990.798      370100.714     1612371.611      370543.562
     1612524.314       370690.81
#Sta/Elev= 30
    10.1  840.17   130.9  816.38   211.5  801.67   251.8  792.87     292  783.64
   302.1  781.76   312.2  780.34   352.5  777.39   372.6  775.41   382.7  773.95
   392.7  771.46   402.8  768.31   407.9  767.22   412.9  766.15   422.9  765.94
   437.9  767.22   463.2  769.94   473.3  771.49   483.4  774.72   503.5  783.23
   523.6  790.41   604.3  816.46   624.5  822.53   634.6  825.07   644.7  826.68
     675  829.11   715.4  833.75   735.6  835.69     776  838.29   796.2  838.68
#Mann= 3 , 0 , 0
       0      .1       0   407.9    .045       0   437.9      .1       0
Bank Sta=407.9,437.9
XS Rating Curve= 0 ,0
Exp/Cntr=0.3,0.1

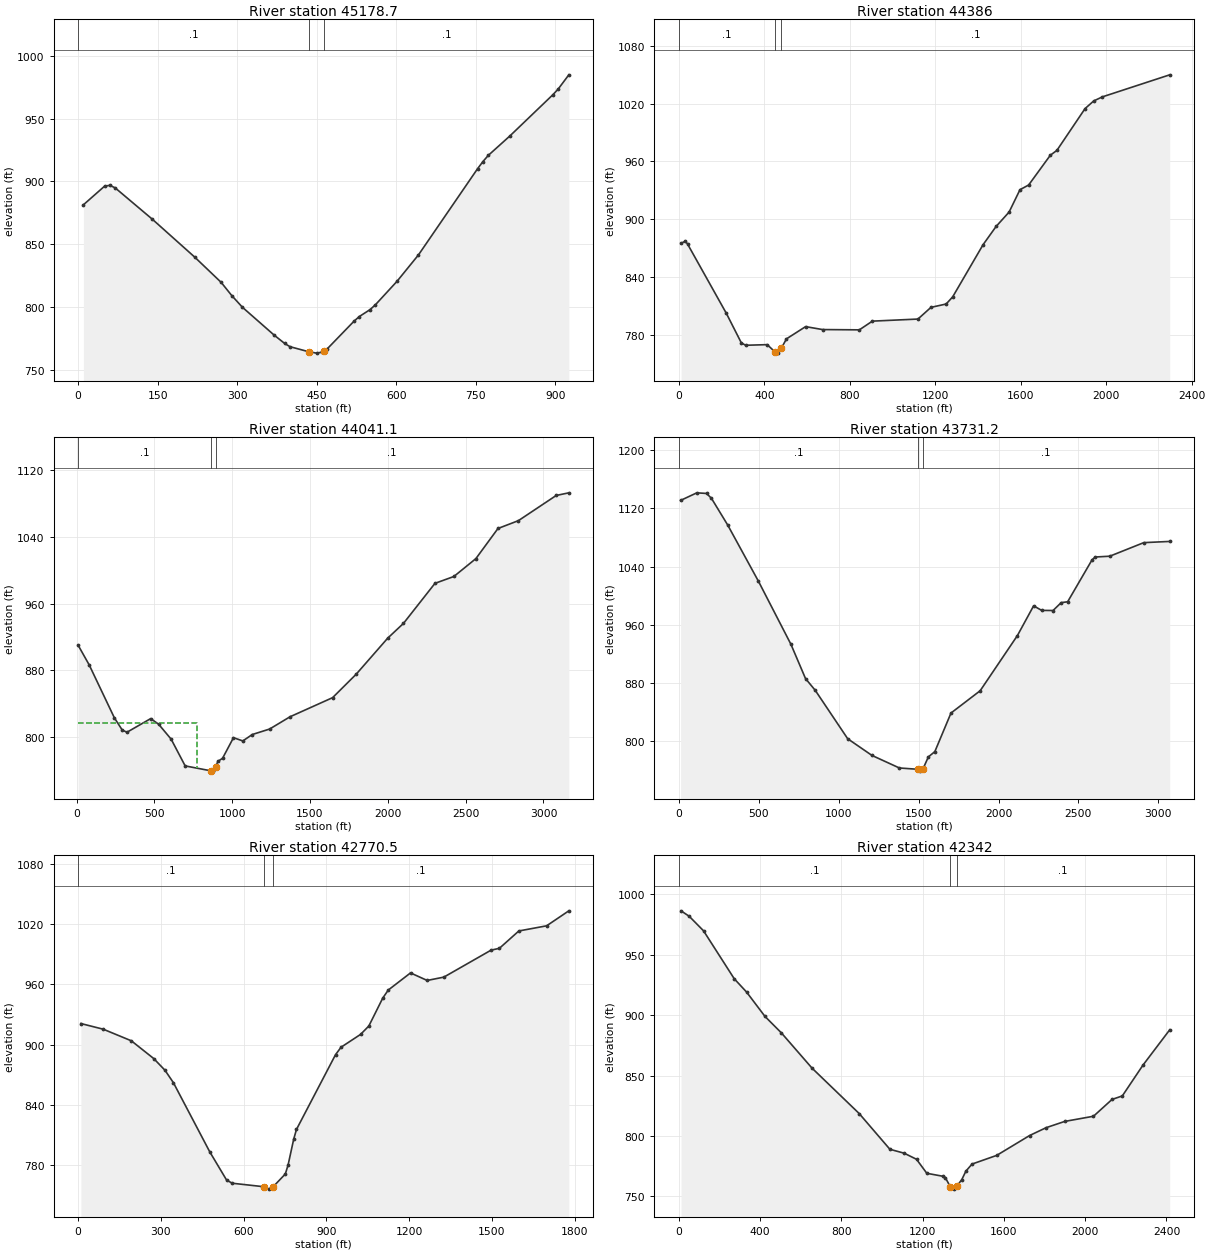
Type RM Length L Ch R = 1 ,45178.7 ,752.4,792.6,835.1
XS GIS Cut Line= 3
     1612224.363      371356.156     1612553.989      371021.606
     1612873.347      370696.264
#Sta/Elev= 30
      10  881.37      50  896.23      60  896.89    69.9  894.89   139.9  869.96
   219.8   839.8   269.8  819.64   289.8  809.13   309.8  799.85   369.7  777.65
   389.7  770.95   399.7   768.4   434.7  764.41   449.7  763.28   459.7  764.04
   464.7  765.32   469.7  766.61   520.3  788.68   530.4  792.43   550.7  797.95
   560.8  801.81   601.4  820.43   641.9  841.48   753.3  910.08   763.5  915.82
   773.6  920.74   814.1  936.12   895.2  968.96   905.3   973.5   925.5  984.89
#Mann= 3 , 0 , 0
       0      .1       0   434.7    .045       0   464.7      .1       0
Bank Sta=434.7,464.7
XS Rating Curve= 0 ,0
Exp/Cntr=0.3,0.1

Type RM Length L Ch R = 1 ,44386   ,335.9,344.9,351.8
XS GIS Cut Line= 4
     1612251.631      371448.868      1612648.64      371687.832
     1612843.713      371825.353      1614369.01      372291.627
#Sta/Elev= 30
    10.1  874.89    30.2  877.09    40.3  874.07   221.6  802.15   292.1  771.32
   312.3  768.91     413  769.55   448.4  762.22   463.4  760.74   478.4  765.58
   503.2  775.58   592.7  788.28   672.2  785.23   844.3  784.93   905.2  793.98
  1118.6  796.15  1179.5   808.3  1250.6  811.79  1281.1  819.19  1423.3  873.39
  1484.3  892.36  1545.3  907.37  1596.1  930.58  1636.7  935.44  1738.3  966.42
  1768.8   971.4  1900.8 1014.88  1941.5 1022.85  1982.1 1027.07    2297 1049.95
#Mann= 3 , 0 , 0
       0      .1       0   448.4    .045       0   478.4      .1       0
Bank Sta=448.4,478.4
XS Rating Curve= 0 ,0
Exp/Cntr=0.3,0.1

Type RM Length L Ch R = 1 ,44041.1 ,299.8,309.9,320
XS GIS Cut Line= 4
     1611872.262      371311.674     1612264.243      371763.305
     1612579.532      372112.679     1612945.949       374174.84
#Sta/Elev= 30
    10.1  910.39    81.1  886.84   243.3  823.26   293.9   808.6   324.3     806
   476.4   822.3   527.1  815.71     608  797.72   698.1  765.65   863.4  759.77
   878.4  759.39   893.4  764.24   908.4  771.08   938.5  774.82  1008.5  799.47
  1068.6  795.58  1129.3  803.27  1240.6  809.82  1372.2  824.57  1645.4  847.45
  1797.1  875.58  1999.5  918.77  2100.7  936.46    2303  984.44  2424.5  992.66
  2566.1 1014.11  2707.8 1050.19  2839.3  1059.6  3082.1 1089.78  3163.1 1092.93
#Mann= 3 , 0 , 0
    10.1      .1       0   863.4    .045       0   893.4      .1       0
#XS Ineff= 2 , 0
          773.91  816.78
Permanent Ineff=
       F       F
Bank Sta=863.4,893.4
XS Rating Curve= 0 ,0
Exp/Cntr=0.3,0.1

Type RM Length L Ch R = 1 ,43731.2 ,971.3,960.7,950
XS GIS Cut Line= 4
      1611216.12      370970.821     1612034.167      371746.262
     1612238.679      372240.499     1612562.489      373612.432
#Sta/Elev= 30
    10.2 1131.07   111.7 1141.51   172.6 1140.65   203.1 1134.04   304.6  1097.4
   497.6 1019.87   700.7  933.27   792.1  886.11     853  869.93  1056.1  803.36
  1207.9  780.43  1379.5  763.17  1495.7  761.35  1510.7  758.83  1525.7  761.12
  1561.1  778.41  1601.5  785.64  1702.6  838.69  1885.2  869.35  2118.4  945.25
  2219.8  986.11  2270.5  979.84  2341.5   979.7  2392.2   990.5  2432.8   991.7
  2584.9 1049.14  2605.2 1053.25  2696.5 1054.36  2909.4 1073.02  3071.7 1074.68
#Mann= 3 , 0 , 0
       0      .1       0  1495.7    .045       0  1525.7      .1       0
Bank Sta=1495.7,1525.7
XS Rating Curve= 0 ,0
Exp/Cntr=0.3,0.1

Type RM Length L Ch R = 1 ,42770.5 ,419.4,428.5,437.4
XS GIS Cut Line= 4
     1611396.655      372202.642     1611471.759      372581.352
      1611795.57      372930.726     1612434.669      373586.868
#Sta/Elev= 30
    10.2  921.01    91.4  915.36     193  903.83   274.3  886.13     315  874.49
   345.4  862.16   477.3  793.26   538.1  765.27   558.4  762.08   675.1  758.53
   690.1   756.2   705.1  758.06     751  771.27   761.1  780.26   781.4  805.98
   791.5  815.66   932.9  889.99     953  897.45  1023.5  910.17  1053.7  918.57
    1104  946.31  1124.1  954.36  1204.7   971.4  1265.1   963.9  1325.5  967.21
  1496.6  994.06  1526.8  995.89  1597.2 1013.15  1697.9 1018.28  1778.4  1033.2
#Mann= 3 , 0 , 0
       0      .1       0   675.1    .045       0   705.1      .1       0
Bank Sta=675.1,705.1
XS Rating Curve= 0 ,0
Exp/Cntr=0.3,0.1

Type RM Length L Ch R = 1 ,42342   ,85.4,86.3,87.4
XS GIS Cut Line= 4
     1611368.032      371775.811     1611282.067      372911.776
     1611521.541      373403.005      1612012.77      373943.356
#Sta/Elev= 30
    10.1  986.22    50.4  981.71     121  969.68   272.2  930.02   332.7  919.07
   423.4   898.9   504.1  885.29   655.3  856.08   887.2  818.57  1038.4  789.01
    1109  785.75  1169.6  780.72  1220.2  769.14  1301.1  766.64  1311.3  765.56
  1336.7  757.78  1351.7  756.05  1366.7  758.37  1392.2  763.86  1412.5  770.92
  1442.8  776.78  1564.3  783.96  1726.3  800.39  1807.4  806.86  1898.7  812.03
  2040.7  816.33    2132  830.23  2182.7  833.15  2284.1  858.56    2416  887.82
#Mann= 3 , 0 , 0
       0      .1       0  1336.7    .045       0  1366.7      .1       0
Bank Sta=1336.7,1366.7
XS Rating Curve= 0 ,0
Exp/Cntr=0.3,0.1

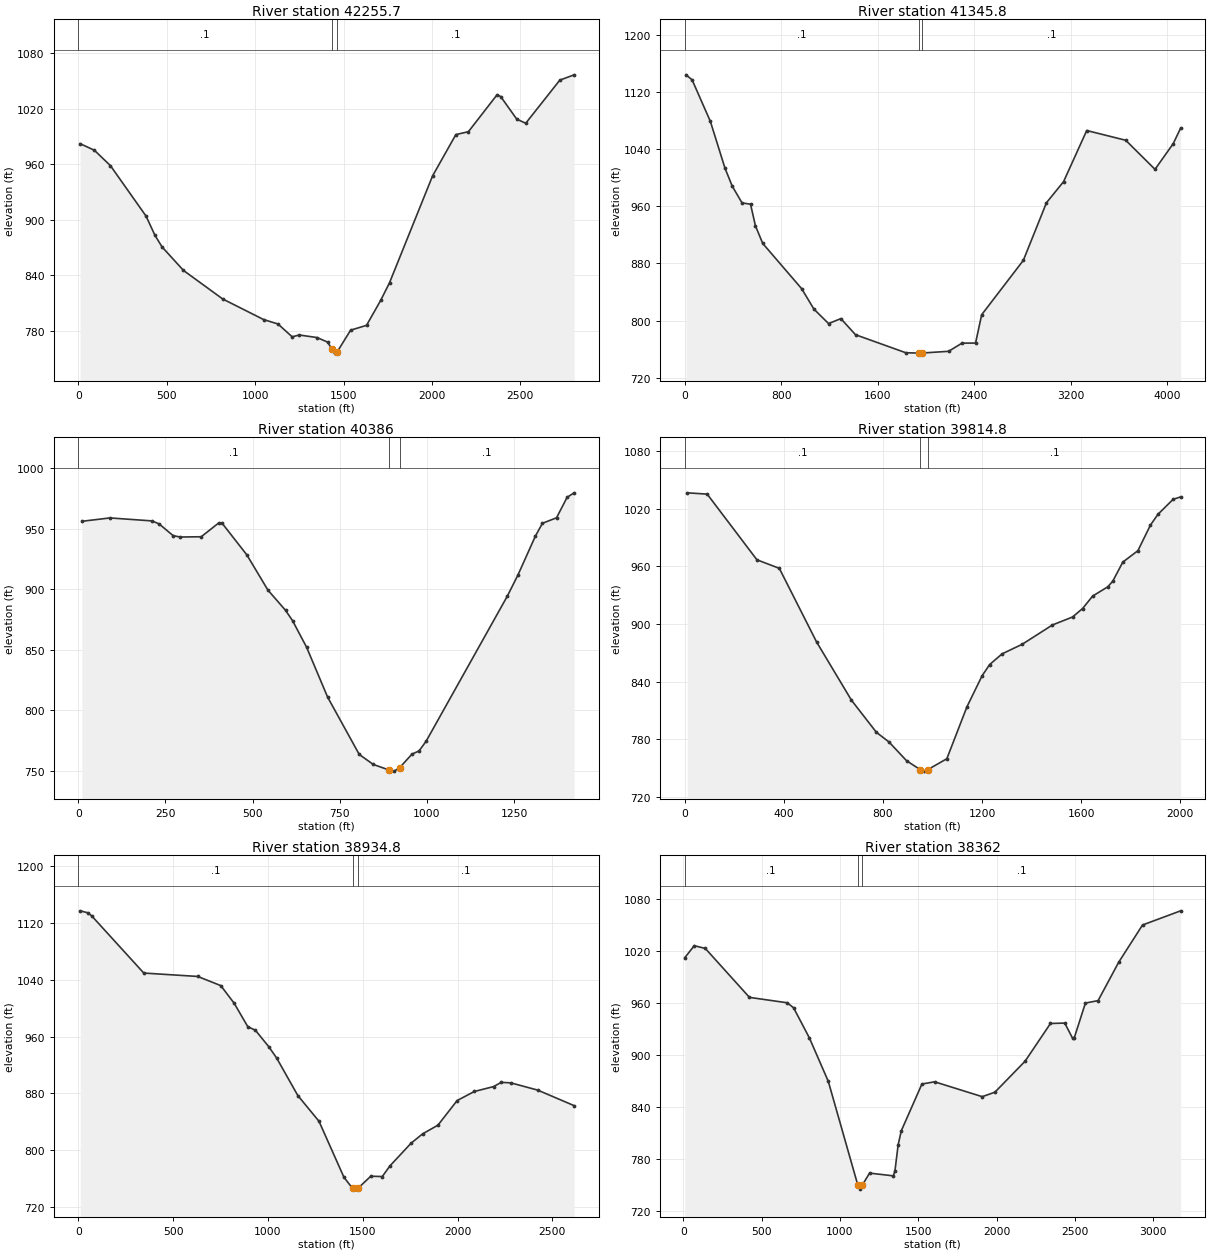
Type RM Length L Ch R = 1 ,42255.7 ,904.1,909.9,915.7
XS GIS Cut Line= 4
     1611341.899      371710.325     1611195.707      372911.161
     1611419.707      373414.179     1611324.856      374454.192
#Sta/Elev= 30
    10.1  982.14    90.7  975.02   181.5  958.38   383.1  903.79   433.5  882.99
   473.8  870.42   594.8  845.02   816.5  814.19  1048.4  791.87  1129.1  787.15
  1209.7  773.22  1249.7  775.21  1349.9  772.46  1409.9  767.56    1435  759.79
    1450   755.6    1465  757.19  1540.1  780.41  1630.2  785.65  1710.3  812.66
  1760.3  831.72  2003.7  947.24  2135.5  991.95  2206.5  995.08  2368.7 1035.03
    2389 1033.12  2480.2  1008.6  2530.9 1004.24  2723.6 1050.86  2804.7 1056.59
#Mann= 3 , 0 , 0
       0      .1       0    1435    .045       0    1465      .1       0
Bank Sta=1435,1465
XS Rating Curve= 0 ,0
Exp/Cntr=0.3,0.1

Type RM Length L Ch R = 1 ,41345.8 ,959.2,959.8,957.9
XS GIS Cut Line= 4
     1610909.352      370595.883     1610653.712      371592.878
     1611020.129      373331.229      1611028.65      374634.992
#Sta/Elev= 30
    10.1 1143.94    60.5 1136.93   211.9 1078.76     333 1013.28   393.5  988.01
   474.3  964.68   544.9   962.8   585.3   932.7   645.8  907.97   968.7  844.54
  1069.9  816.05  1191.7   795.7  1293.2  802.69    1415  780.13  1831.2  754.93
  1938.1  754.42  1953.1  754.36  1968.1  754.51  2186.5  756.91  2298.2  768.39
  2409.9  768.42  2460.6  808.13  2805.8   884.2  2997.8  964.94  3139.3   994.4
  3331.4 1065.98  3654.8 1052.31  3897.3 1011.63  4048.9  1047.8  4109.6  1069.4
#Mann= 3 , 0 , 0
       0      .1       0  1938.1    .045       0  1968.1      .1       0
Bank Sta=1938.1,1968.1
XS Rating Curve= 0 ,0
Exp/Cntr=0.3,0.1

Type RM Length L Ch R = 1 ,40386   ,561.1,571.2,580
XS GIS Cut Line= 3
     1610202.082      372189.371     1610351.209      373083.519
     1610415.115       373595.39
#Sta/Elev= 30
    10.1  955.96    90.6  958.75   211.5  956.29   231.7  953.81   271.9  944.15
   292.1     943   352.5  943.22   402.9  954.65     413  954.17   483.5  928.22
   543.9  899.19   594.3  882.55   614.4  874.01   654.7  852.11   715.1   810.9
   805.8  763.61   846.1  755.34   891.5  750.74   906.5  749.84   921.5  752.64
   957.1  763.85   977.3  766.51   997.5  774.44  1230.2  894.02  1260.5  911.32
  1311.1  943.76  1331.3  954.31  1371.8  958.88  1402.1  975.78  1422.3  979.46
#Mann= 3 , 0 , 0
       0      .1       0   891.5    .045       0   921.5      .1       0
Bank Sta=891.5,921.5
XS Rating Curve= 0 ,0
Exp/Cntr=0.3,0.1

Type RM Length L Ch R = 1 ,39814.8 ,878.3,880,881.7
XS GIS Cut Line= 4
     1609810.101      372129.722     1609827.143      372862.556
     1609758.973      373263.058     1610057.219      374072.584
#Sta/Elev= 30
      10  1036.4    90.4 1035.06   291.2  966.73   381.6  957.86   532.2  881.21
   672.8   820.7   773.7  787.23   824.4  777.23   895.5  757.69   951.6  748.26
   966.6  746.88   981.6  748.52    1058  759.76  1139.3  813.85  1200.2  845.98
  1230.6  857.69  1281.4  868.92  1362.6  878.88  1484.4  898.93  1565.6  907.21
  1606.2  916.05  1646.8  928.99  1707.7   938.6    1728  944.49  1768.6  964.34
  1829.5   976.2  1880.2 1002.89  1910.7 1014.09  1971.6 1029.65    2002 1032.15
#Mann= 3 , 0 , 0
       0      .1       0   951.6    .045       0   981.6      .1       0
Bank Sta=951.6,981.6
XS Rating Curve= 0 ,0
Exp/Cntr=0.3,0.1

Type RM Length L Ch R = 1 ,38934.8 ,610.8,572.8,534.8
XS GIS Cut Line= 4
     1608932.404       371286.11     1609060.224      372538.745
     1608975.011      372913.684     1609571.504      373680.603
#Sta/Elev= 30
    10.2 1136.76    50.8 1133.95    71.1 1129.49   345.2 1049.29   629.6 1044.52
   751.4 1031.63   822.5 1006.63   893.6  973.97   934.2  968.82  1005.3  945.47
  1045.9   929.9  1157.6  877.16  1269.3  840.97  1400.8  762.32  1446.5  746.53
  1461.5  745.56  1476.5  747.15  1542.5  763.69  1603.2  763.26  1643.6  778.25
    1755   810.1  1815.7  823.23  1896.7  835.44  1997.9  870.05  2088.9  882.84
  2190.2  889.68  2230.6  895.66  2281.2  894.94  2422.9  884.75  2615.2  862.89
#Mann= 3 , 0 , 0
       0      .1       0  1446.5    .045       0  1476.5      .1       0
Bank Sta=1446.5,1476.5
XS Rating Curve= 0 ,0
Exp/Cntr=0.3,0.1

Type RM Length L Ch R = 1 ,38362   ,1620.5,1626.3,1631.9
XS GIS Cut Line= 4
     1608208.091      372001.902     1608412.603      372905.162
     1608787.541      373126.717     1609963.485      374507.172
#Sta/Elev= 30
    10.1 1012.05    70.5 1025.83   140.9 1022.69   422.8  966.29   664.4  960.05
   704.7  954.24   805.3  919.61   926.1  869.52  1113.7  750.55 1129.38  745.38
  1143.7  750.15  1189.5  763.84  1341.4  760.66  1351.5  766.34  1371.8  796.17
    1392  812.57  1523.7  866.47  1604.8  869.02  1908.7   851.9  1989.7  857.06
  2182.2  892.74  2344.3   936.2  2435.5  936.69  2486.2  918.93  2496.3  919.74
  2567.2  959.71  2648.2  962.56  2779.9 1006.82  2931.9 1049.67  3175.1    1066
#Mann= 3 , 0 , 0
    10.1      .1       0  1113.7    .045       0  1143.7      .1       0
Bank Sta=1113.7,1143.7
XS Rating Curve= 0 ,0
Exp/Cntr=0.3,0.1

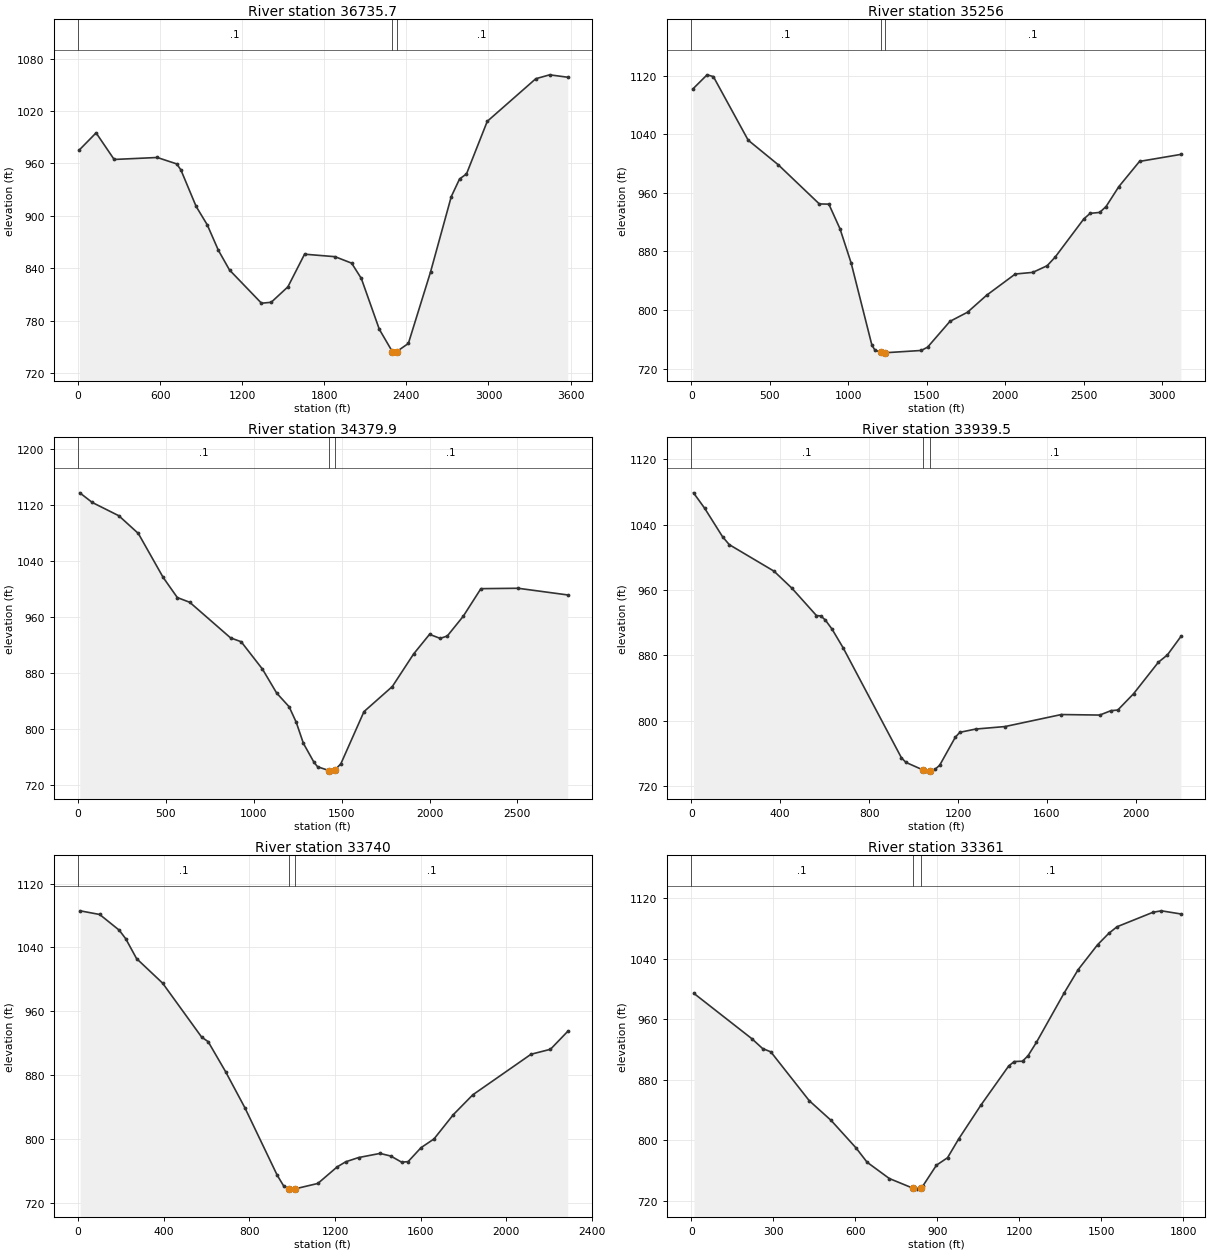
Type RM Length L Ch R = 1 ,36735.7 ,1481.7,1479.7,1477.8
XS GIS Cut Line= 4
     1608097.314      372138.243     1608506.338      373774.337
     1609477.769      374583.864     1609954.963      374992.887
#Sta/Elev= 30
    10.2  975.61   132.1  995.04   264.1   964.6   579.1  966.86   721.3  959.52
   751.8  952.68   863.5  910.82   944.8  889.74  1026.1   860.6  1107.4  838.07
    1341  800.07  1412.1   801.1  1534.1  818.78    1656  856.17  1878.7  853.31
    2000  845.92  2070.9   828.4  2202.4  770.22  2298.6  744.41  2313.6  742.92
  2328.6  744.58  2414.8     754  2576.7  835.71  2728.4  922.09  2789.1   942.3
  2839.7  948.03  2991.5 1008.25  3346.3 1057.03  3447.7 1061.48  3579.5 1058.73
#Mann= 3 , 0 , 0
       0      .1       0  2298.6    .045       0  2328.6      .1       0
Bank Sta=2298.6,2328.6
XS Rating Curve= 0 ,0
Exp/Cntr=0.3,0.1

Type RM Length L Ch R = 1 ,35256   ,912.3,876.1,839.8
XS GIS Cut Line= 4
     1606682.774      373510.176     1607500.821      373680.603
     1608208.091      374225.968     1609366.992      374992.887
#Sta/Elev= 30
    10.1 1101.62   100.7 1120.93   140.9  1118.5   362.4 1031.77   553.7  998.28
   815.5  944.77   876.2  944.49   947.3  910.81  1018.3  864.11  1150.2  752.21
  1170.5  744.98  1206.3   742.7  1221.3  741.19  1236.3  741.72  1464.9  744.83
  1505.4   749.4  1647.5  784.54  1759.2     797  1880.9  820.16  2063.5  849.15
    2175  851.38  2266.3  860.43  2317.1  872.13  2499.6  924.24  2540.2   931.9
  2601.1  933.19  2641.7  941.24  2722.8  968.33  2854.7  1002.8  3118.4 1012.37
#Mann= 3 , 0 , 0
       0      .1       0  1206.3    .045       0  1236.3      .1       0
Bank Sta=1206.3,1236.3
XS Rating Curve= 0 ,0
Exp/Cntr=0.3,0.1

Type RM Length L Ch R = 1 ,34379.9 ,408.5,440.4,472.4
XS GIS Cut Line= 4
     1606998.063      374277.096     1608037.665      374720.205
     1608463.731      374464.565     1609401.077      375146.271
#Sta/Elev= 30
    10.1 1137.38    80.7 1123.64   232.1 1104.62   343.1 1079.29   484.3 1016.47
     565  987.64   635.7  980.88   867.8  930.02   928.3  924.47  1049.4  885.32
  1130.1  851.13  1201.1  831.51  1241.6  809.31  1282.2  779.24    1343   751.9
  1363.3  745.68  1429.4   740.2  1444.4  739.49  1459.4  740.73  1495.1  749.84
    1627  824.58  1788.2  860.44  1909.2  906.95  1999.9  935.05  2060.3  929.29
  2100.7  932.62  2191.4  960.81  2292.2 1000.37  2503.8 1000.93    2786  991.38
#Mann= 3 , 0 , 0
       0      .1       0  1429.4    .045       0  1459.4      .1       0
Bank Sta=1429.4,1459.4
XS Rating Curve= 0 ,0
Exp/Cntr=0.3,0.1

Type RM Length L Ch R = 1 ,33939.5 ,197,199.5,202
XS GIS Cut Line= 4
     1607331.118       374485.19     1608146.557      374878.172
     1608426.557      375040.278      1609227.26      375595.366
#Sta/Elev= 30
    10.1 1078.85    60.3 1059.98   140.8 1025.13     171 1015.45   372.1  983.02
   452.6  962.21   563.2  928.67   583.3  928.18   603.5  923.08   633.6  911.96
   683.9   888.9   945.6  754.59   965.9  748.98  1041.9   739.8  1056.9  738.29
  1071.9  738.48  1097.3   740.7  1117.5  745.43  1188.3  779.95  1208.5  785.78
  1279.5  789.77  1411.4  792.83  1665.1  807.54  1837.7   806.9  1888.4  812.29
  1918.9  813.04  1989.9     833  2101.5  871.54  2142.1  880.48    2203   903.1
#Mann= 3 , 0 , 0
       0      .1       0  1041.9    .045       0  1071.9      .1       0
Bank Sta=1041.9,1071.9
XS Rating Curve= 0 ,0
Exp/Cntr=0.3,0.1

Type RM Length L Ch R = 1 ,33740   ,368.1,379,388.7
XS GIS Cut Line= 4
     1607298.615      374602.209     1608014.407      375002.712
     1608414.909      375283.916     1609181.828       375888.93
#Sta/Elev= 30
    10.1 1085.88   101.3 1081.29   192.4 1061.61   222.8 1050.87   273.4 1025.99
   394.9  995.26   577.2  927.59   607.6  921.88   688.6  884.45   779.7  838.71
   930.1  754.41     960  741.06     985  737.36    1000  737.01    1015  737.45
  1119.8  744.13  1209.7  764.82  1249.7  771.25  1309.6  776.57  1410.3  781.78
  1460.6  778.46    1511  770.79  1541.2  771.48  1601.6  788.99  1662.1  799.91
  1752.7  830.48  1843.3  855.24  2115.2  906.09  2205.9  912.31  2286.4  934.74
#Mann= 3 , 0 , 0
       0      .1       0     985    .045       0    1015      .1       0
Bank Sta=985,1015
XS Rating Curve= 0 ,0
Exp/Cntr=0.3,0.1

Type RM Length L Ch R = 1 ,33361   ,975.5,973.2,973.5
XS GIS Cut Line= 4
     1607483.779      374813.939     1607850.196      375240.006
     1608088.793      375529.731     1608301.826      376356.299
#Sta/Elev= 30
      10  994.18   220.8  934.61   260.9  921.38     291  916.99   431.5  852.47
   511.8  826.28   602.5  790.12   643.1  771.13   724.3  749.63   810.7  736.82
   825.7  735.59   840.7  737.68     846  739.19   896.7   767.2   937.3  777.09
   977.9   801.8  1059.2  846.52  1160.8  898.25  1181.2  904.19  1211.6  904.63
    1232  912.01  1262.5  929.62  1364.1  994.97  1414.9 1025.56    1486 1058.53
  1526.7 1073.46  1557.1 1082.29  1689.2  1101.5  1719.7 1103.35  1790.9 1099.19
#Mann= 3 , 0 , 0
       0      .1       0   810.7    .045       0   840.7      .1       0
Bank Sta=810.7,840.7
XS Rating Curve= 0 ,0
Exp/Cntr=0.3,0.1

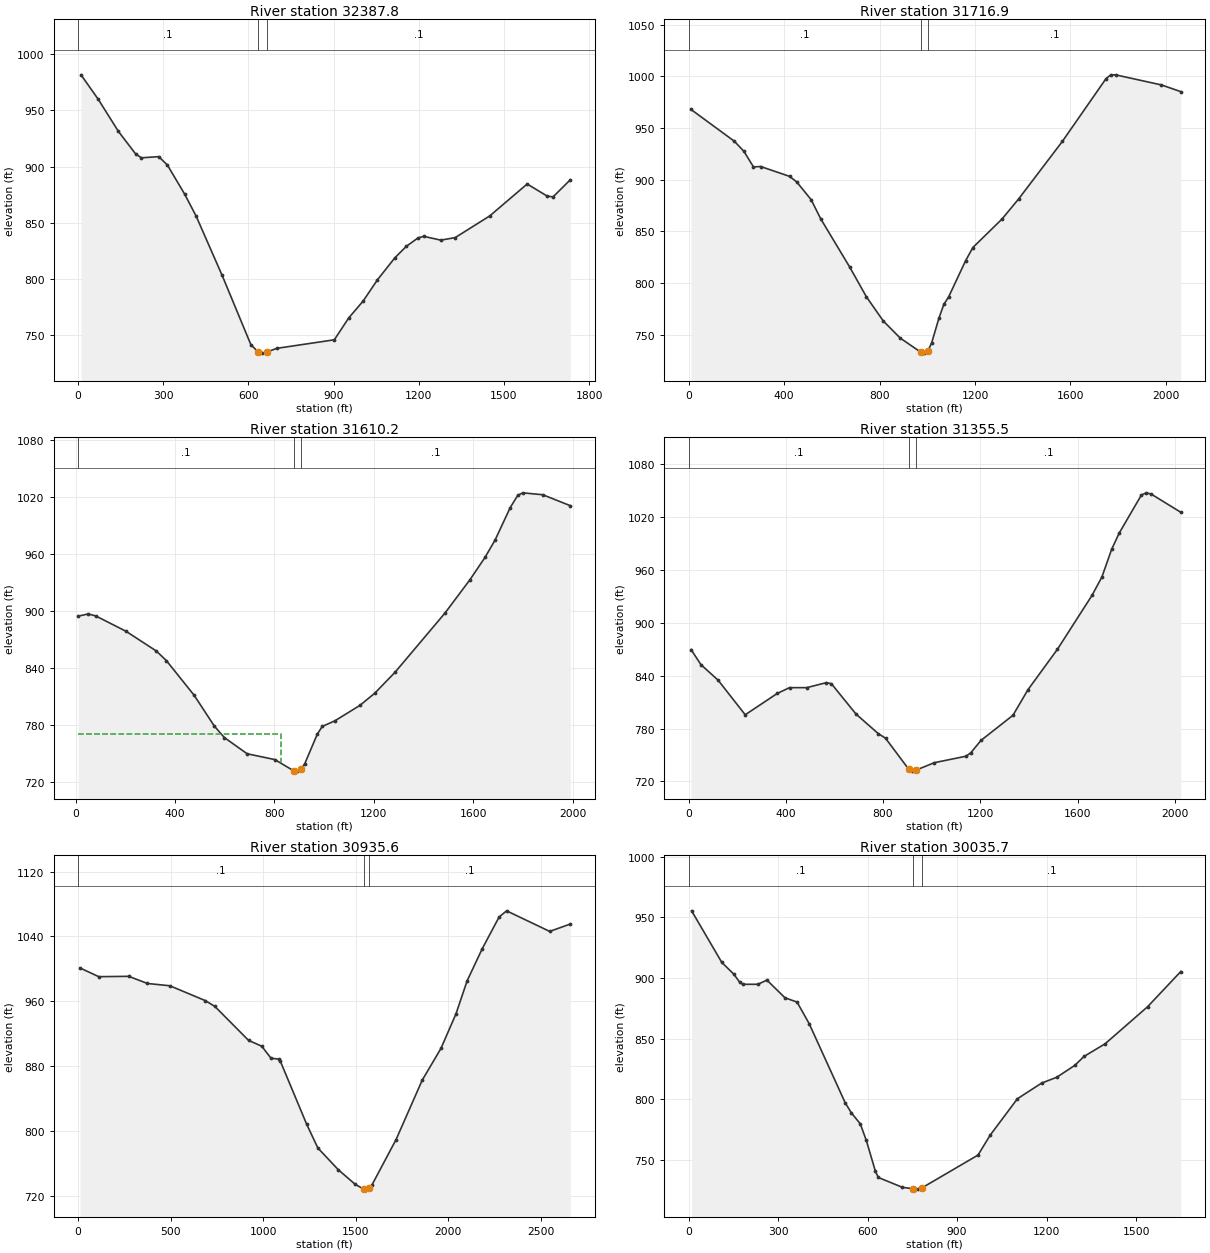
Type RM Length L Ch R = 1 ,32387.8 ,679.7,670.9,660.7
XS GIS Cut Line= 3
     1606691.295       375009.93     1607098.452      375515.037
     1607739.418      376390.385
#Sta/Elev= 30
    10.1  981.53      71  959.69   141.9  931.24   202.7  911.15     223  907.78
   283.8  908.85   314.3  901.38   375.1  875.54   415.6  855.99   506.9  803.48
   608.2  741.87   633.8  735.31   648.8  734.24   663.8  735.13   699.5  738.48
   902.3  746.08     953   765.5  1003.7  780.48  1054.4  799.45  1115.2  818.81
  1155.8  829.13  1196.3  836.45  1216.6  838.03  1277.4  834.64  1328.1   836.9
  1449.8  856.17  1581.6  884.53  1652.6  873.69  1672.9  873.12  1733.7   888.3
#Mann= 3 , 0 , 0
       0      .1       0   633.8    .045       0   663.8      .1       0
Bank Sta=633.8,663.8
XS Rating Curve= 0 ,0
Exp/Cntr=0.3,0.1

Type RM Length L Ch R = 1 ,31716.9 ,106.2,106.7,107.1
XS GIS Cut Line= 4
     1606035.153      375538.252     1606640.167      375989.882
     1607100.319      376305.171     1607739.418      376697.152
#Sta/Elev= 30
    10.1  967.93   191.3  937.25   231.5   927.5   271.8  912.37     302  912.74
   422.8  903.22     453  897.85   513.4  880.68   553.7   862.1   674.5  815.69
   744.9  786.76   815.8  763.32   886.8  746.76   973.3  733.08   988.3  732.22
  1003.3  734.56  1018.7  742.27  1049.1  766.17  1069.4  779.28  1089.7  786.68
  1160.7  821.59  1191.1  834.37  1312.8   861.8  1383.7  881.58  1566.1  937.01
  1748.5  997.53  1768.7 1001.38    1789 1001.42  1981.5  991.64  2062.5  985.15
#Mann= 3 , 0 , 0
       0      .1       0   973.3    .045       0  1003.3      .1       0
Bank Sta=973.3,1003.3
XS Rating Curve= 0 ,0
Exp/Cntr=0.3,0.1

Type RM Length L Ch R = 1 ,31610.2 ,274.9,254.6,234.6
XS GIS Cut Line= 4
     1606014.626      375708.349     1606677.784       376140.63
     1606898.837      376297.823     1607709.364      376749.753
#Sta/Elev= 30
    10.1  894.87    50.7  897.21    81.2   895.1     203  878.95   324.8  858.22
   365.4  848.09     477  811.67   558.2  779.26   598.8  767.16   690.1   750.2
   801.7  744.07   877.1  732.33   892.1  731.93   907.1  733.73   922.2  739.79
   972.4  770.77   992.5  778.94  1042.8  784.77  1143.6  800.99  1204.1  813.96
  1284.8  835.72  1486.5  898.19  1587.4  933.41  1647.9  956.86  1688.3  975.11
  1748.8 1009.01    1779 1021.85  1799.2 1024.58  1879.9 1022.57  1990.9 1011.03
#Mann= 3 , 0 , 0
    10.1      .1       0   877.1    .045       0   907.1      .1       0
#XS Ineff= 2 , 0
          824.54  771.24
Permanent Ineff=
       F       F
Bank Sta=877.1,907.1
XS Rating Curve= 0 ,0
Exp/Cntr=0.3,0.1

Type RM Length L Ch R = 1 ,31355.5 ,424.5,419.9,415.3
XS GIS Cut Line= 4
     1605823.047      376125.893     1606569.714      376440.279
      1606839.89      376425.542     1607709.364      376793.963
#Sta/Elev= 30
    10.1  869.48    50.6  852.39   121.5  834.72   232.9  795.54   364.6   819.7
   415.2  826.29   486.1  826.29   567.1  831.99   587.4  830.75   688.6  796.41
   779.8  774.33   810.2  768.99   905.4  733.92   920.4  731.71   935.4  732.81
  1010.6  741.25  1141.7  748.63    1162  752.77  1202.6  766.44  1334.6  795.01
  1395.5  823.66  1517.3  869.72  1659.5  930.72  1700.1  951.49  1740.7  983.14
  1771.2 1001.21  1862.6 1044.41  1882.9    1047  1903.2 1045.57    2025 1024.97
#Mann= 3 , 0 , 0
       0      .1       0   905.4    .045       0   935.4      .1       0
Bank Sta=905.4,935.4
XS Rating Curve= 0 ,0
Exp/Cntr=0.3,0.1

Type RM Length L Ch R = 1 ,30935.6 ,886.5,899.9,914.6
XS GIS Cut Line= 4
     1605413.096      376526.726     1606691.295      376790.887
     1607202.575       376680.11     1607952.452      377038.005
#Sta/Elev= 30
    10.1 1000.94   111.3  990.18   273.2   990.6   374.4  981.79   495.8  978.93
     688  960.51   738.6  953.45   920.7  911.54   991.6  904.35  1042.1  889.53
  1082.6  888.39  1092.7  885.67  1234.4  808.12  1295.1  778.69  1405.8  751.74
  1496.4  733.88  1541.7  728.08  1556.7  727.87  1571.7  728.78  1586.9  732.83
  1717.7  789.08  1858.8  862.35  1960.1  901.58  2041.1  944.15  2101.9  985.21
    2183 1024.62  2274.2  1063.8  2314.7 1071.48  2547.8 1046.07  2659.3 1055.19
#Mann= 3 , 0 , 0
       0      .1       0  1541.7    .045       0  1571.7      .1       0
Bank Sta=1541.7,1571.7
XS Rating Curve= 0 ,0
Exp/Cntr=0.3,0.1

Type RM Length L Ch R = 1 ,30035.7 ,534.9,546,555.7
XS GIS Cut Line= 3
     1606197.058      377447.029     1606963.978      377625.977
     1607782.025       377898.66
#Sta/Elev= 30
    10.1  955.25   111.1   912.8   151.4  903.08   171.6   896.3   181.7  894.71
   232.2  894.71   262.5  898.17   323.1  883.58   363.5  880.06   403.9   862.4
     525  797.03   545.2   788.9   575.5   779.7   595.7  766.01     626  740.75
   636.1  735.51   716.8  727.38   752.3  726.26   767.3  725.92   782.3  726.98
   970.1  753.99  1010.7  770.34    1102  800.37  1183.2  813.29  1233.9  818.09
  1294.8  827.95  1325.2  835.23  1396.2  845.71  1538.2  876.16  1649.8  905.25
#Mann= 3 , 0 , 0
       0      .1       0   752.3    .045       0   782.3      .1       0
Bank Sta=752.3,782.3
XS Rating Curve= 0 ,0
Exp/Cntr=0.3,0.1