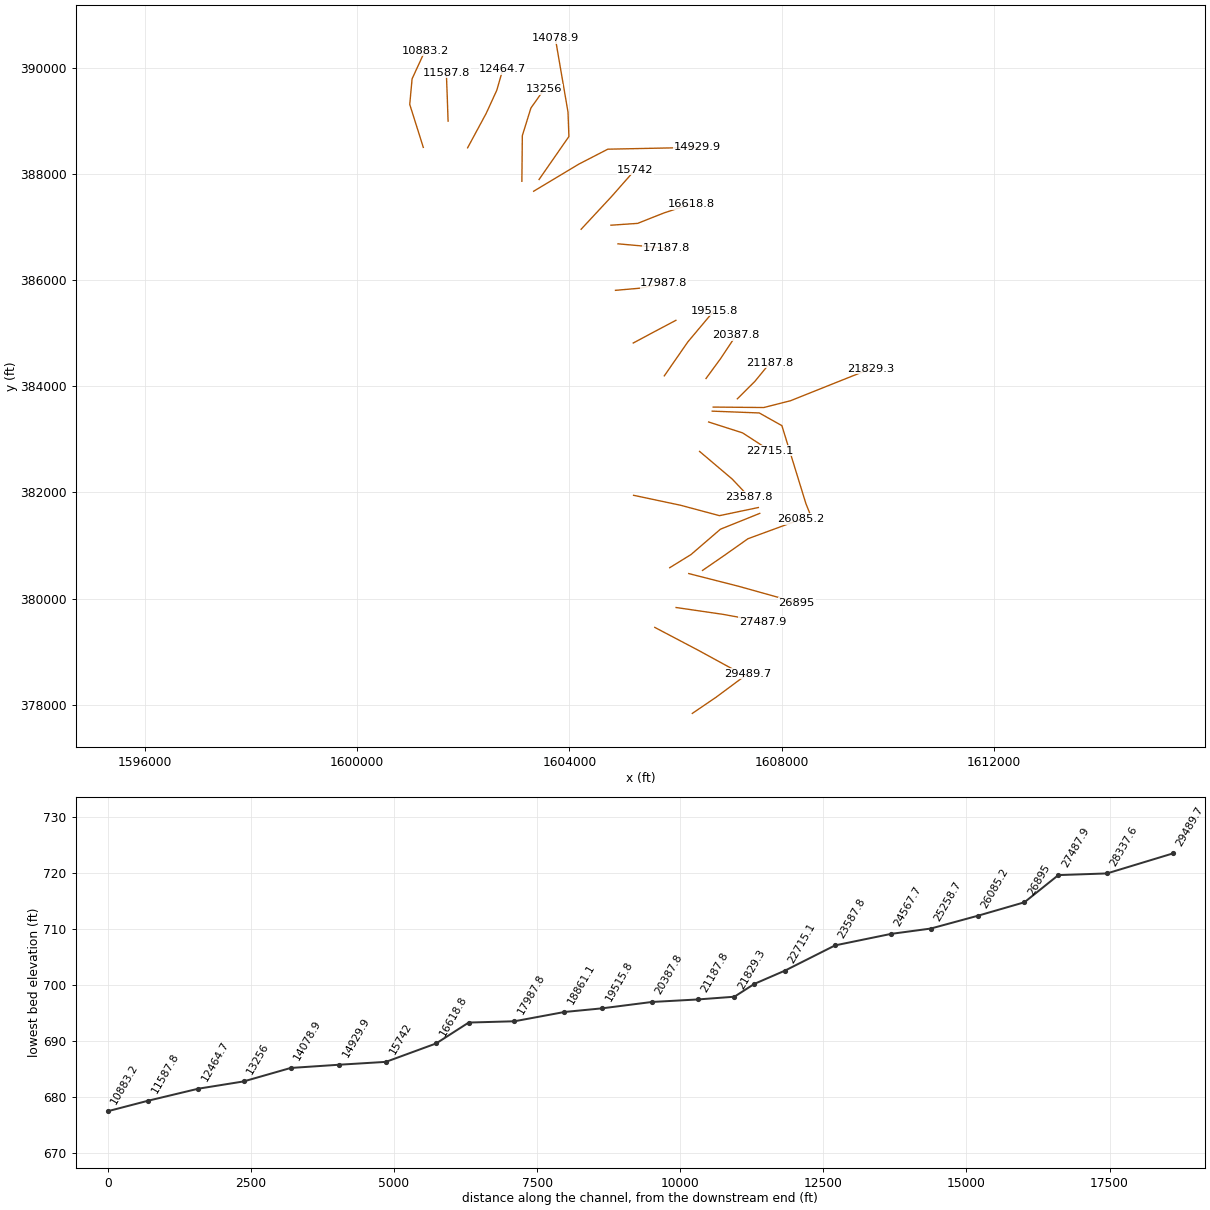
HEC-RAS study KIAHCR.prj: KIAHCR

--- KIAHCR.g01 (geometry) --- (continued)

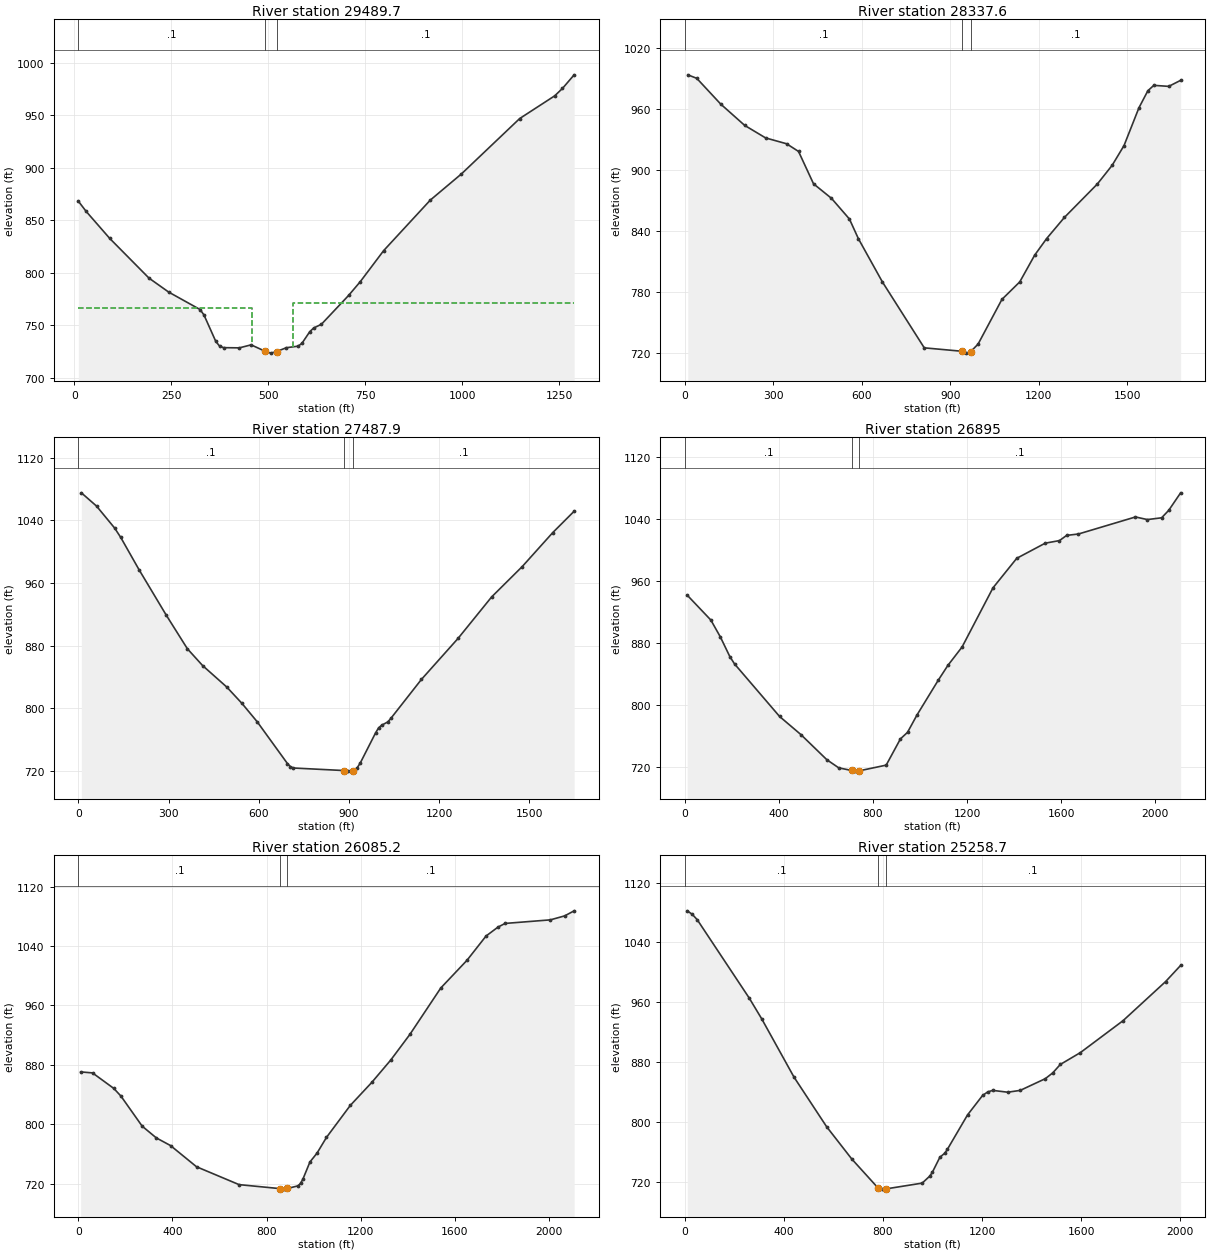
Type RM Length L Ch R = 1 ,29489.7 ,1185,1152.1,1119.1
XS GIS Cut Line= 3
     1606316.357       377839.01     1606760.301      378140.771
      1607364.48      378588.887
#Sta/Elev= 30
    10.1  868.29    30.4  858.48    91.2  832.76   192.4  794.99   243.1  781.71
   324.1  765.09   334.2  759.89   364.6  734.77   374.7  730.13   384.9  728.78
   425.4  728.59   455.8  731.46   491.4  725.42   506.4  723.57   521.4  725.06
   546.8  728.74   576.9  730.19   586.9  732.93     607  743.94     617  747.47
   637.1  751.06   707.3  778.54   737.4  791.65   797.6  821.17   917.9  869.28
   998.2  894.21  1148.6  946.99  1238.9  968.61  1258.9  975.66    1289  988.59
#Mann= 3 , 0 , 0
    10.1      .1       0   491.4    .045       0   521.4      .1       0
#XS Ineff= 2 , 0
          459.15  766.19  564.38          771.02
Permanent Ineff=
       F       F
Bank Sta=491.4,521.4
XS Rating Curve= 0 ,0
Exp/Cntr=0.3,0.1

Type RM Length L Ch R = 1 ,28337.6 ,839.2,849.7,859.5
XS GIS Cut Line= 3
     1605609.087      379458.062     1606435.656      379023.475
     1607091.798      378665.579
#Sta/Elev= 30
    10.2  993.62    40.6  990.18   121.8  964.85     203  943.92   274.1  931.58
   345.1  925.85   385.7  918.28   436.5  886.47   497.4  872.19   558.3  851.82
   588.7  832.47   669.9  790.06     812  725.19   939.1  721.84   954.1  719.99
   969.1  721.36   994.5  728.87  1075.3   772.8  1135.9  790.05  1186.4  816.32
  1226.8  832.57  1287.4  853.47  1398.5  886.14    1449   904.6  1489.4  924.08
  1539.9  961.18  1570.2  977.97  1590.4  983.27  1640.9  982.27  1681.3  988.19
#Mann= 3 , 0 , 0
       0      .1       0   939.1    .045       0   969.1      .1       0
Bank Sta=939.1,969.1
XS Rating Curve= 0 ,0
Exp/Cntr=0.3,0.1

Type RM Length L Ch R = 1 ,27487.9 ,595.8,592.9,590.8
XS GIS Cut Line= 3
     1606009.589         379833.     1606887.286      379705.181
     1607637.162      379568.839
#Sta/Elev= 30
    10.1 1075.28    60.5 1058.37   120.9 1030.18   141.1 1018.26   201.6  977.26
   292.3  919.06   362.8  875.98   413.2  854.61   493.9  827.06   544.3   806.2
   594.7  782.86   695.5  729.35   705.5  725.34   715.6  723.68   882.1  720.45
   897.1  719.69   912.1  720.15   927.6  724.02   937.8  730.15   988.6  768.53
   998.7  774.98  1008.9  778.36  1029.2  782.53  1039.4  787.06    1141  836.82
    1263  889.29  1374.7  942.29  1476.4  981.06    1578  1024.5  1649.1 1051.79
#Mann= 3 , 0 , 0
       0      .1       0   882.1    .045       0   912.1      .1       0
Bank Sta=882.1,912.1
XS Rating Curve= 0 ,0
Exp/Cntr=0.3,0.1

Type RM Length L Ch R = 1 ,26895   ,782.5,809.8,836.5
XS GIS Cut Line= 3
     1606248.186        380472.1     1607185.532      380233.503
     1608284.783      379926.735
#Sta/Elev= 30
    10.1  941.72   110.8  909.58   151.1   887.9   191.4  862.58   211.6     853
     403  785.31   493.7  761.95   604.5  729.42   654.9  719.02   710.4  715.64
   725.4  714.83   740.4  715.14   856.4  722.56   916.9  756.36   947.1  764.82
   987.4  787.21  1078.3  832.27  1118.7   851.1  1179.3  874.94  1310.6  951.12
  1411.6  989.19  1532.8  1008.7  1593.4 1012.03  1623.7 1018.71  1674.2 1020.54
  1916.6  1042.5  1967.1 1039.11  2027.7 1041.42    2058 1051.06  2108.5  1073.6
#Mann= 3 , 0 , 0
       0      .1       0   710.4    .045       0   740.4      .1       0
Bank Sta=710.4,740.4
XS Rating Curve= 0 ,0
Exp/Cntr=0.3,0.1

Type RM Length L Ch R = 1 ,26085.2 ,824.2,826.5,829.4
XS GIS Cut Line= 4
     1606507.959      380531.133     1606929.892      380821.474
      1607364.48      381128.242     1608361.475      381494.659
#Sta/Elev= 30
      10  870.37    60.3  869.02   150.6  848.12   180.8  837.85   271.2  797.26
   331.4  781.42   391.7  771.12   502.1  742.57   682.8  718.49   858.5  713.06
   873.5  712.43   888.5  713.35   933.7  716.88   943.8  720.24   953.8  725.71
   983.9  749.03    1014  760.93  1054.2  782.15  1155.4  825.25  1246.5  856.18
  1327.4  886.45  1408.3   920.8  1539.8  983.47  1651.1 1020.78    1732 1053.44
  1782.6 1065.45    1813 1070.42  2005.2 1075.23  2065.9 1080.58  2106.3  1087.4
#Mann= 3 , 0 , 0
       0      .1       0   858.5    .045       0   888.5      .1       0
Bank Sta=858.5,888.5
XS Rating Curve= 0 ,0
Exp/Cntr=0.3,0.1

Type RM Length L Ch R = 1 ,25258.7 ,721.4,691,660.6
XS GIS Cut Line= 4
     1605890.291      380582.877     1606290.793      380829.996
     1606844.679       381307.19     1607586.035      381605.436
#Sta/Elev= 30
      10 1082.14      30  1077.5    50.1 1070.32   260.3  965.37   310.4  937.74
   440.6   859.9   572.1  793.65   673.7  750.43   780.5  711.44   795.5  710.13
   810.5  710.37     958  718.17   988.5  727.54   998.6  732.41  1029.1  752.64
  1049.4  758.28  1059.5  763.26  1140.8  809.28  1201.7  835.37  1221.9  839.95
  1242.2  842.13  1302.9  839.69  1353.4   842.1  1454.6  857.75  1484.9  865.55
  1515.3  876.78  1596.2   892.6  1768.2  935.22  1940.1  987.52  2000.8 1009.15
#Mann= 3 , 0 , 0
       0      .1       0   780.5    .045       0   810.5      .1       0
Bank Sta=780.5,810.5
XS Rating Curve= 0 ,0
Exp/Cntr=0.3,0.1

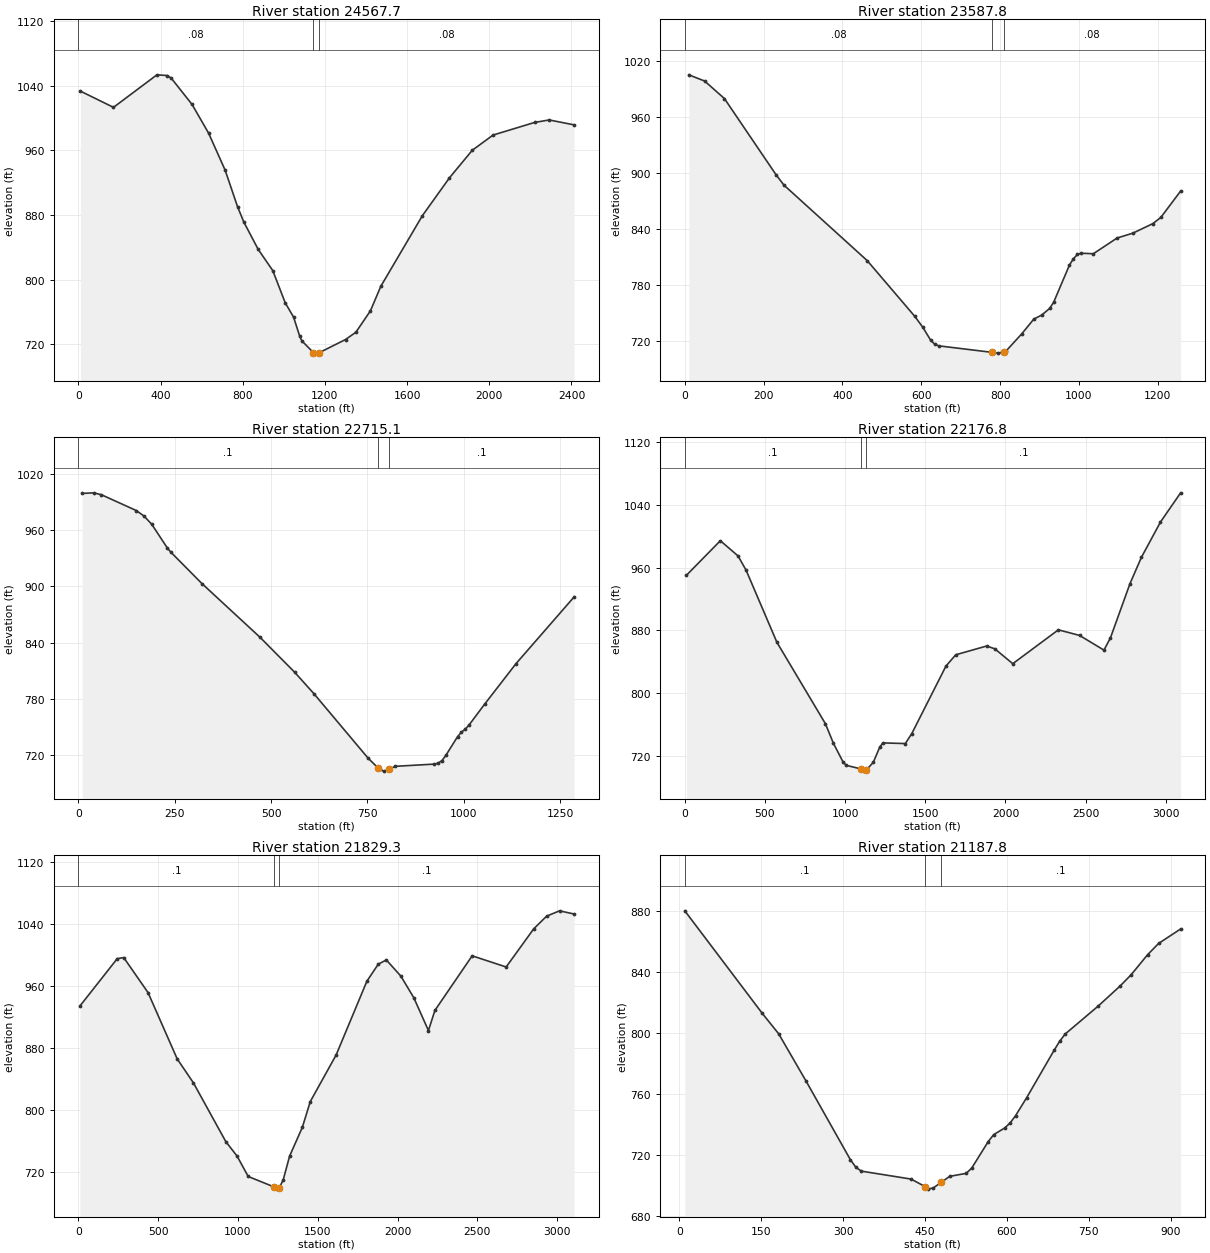
Type RM Length L Ch R = 1 ,24567.7 ,992.9,979.9,963.7
XS GIS Cut Line= 4
     1605208.584       381946.29     1606094.802       381758.82
     1606827.636       381562.83     1607560.471      381716.214
#Sta/Elev= 30
    10.1 1033.24   171.1 1013.18   382.5  1053.4   432.8 1052.54   452.9 1049.07
   553.6 1016.71   634.1   981.2   714.6   935.4     775  890.22   805.2  871.42
   875.6  837.41   946.3  811.29    1007  771.37  1047.4  753.82  1077.8   729.8
  1087.9  724.35  1143.7  709.93  1158.7  709.18  1173.7  709.89  1300.3     726
  1350.9  735.02  1421.7  761.56  1472.2  791.88  1674.5  879.22  1806.1  925.96
  1917.4  960.13  2018.5   978.9  2220.9  994.53  2291.7  997.58  2413.1  991.49
#Mann= 3 , 0 , 0
       0     .08       0  1143.7    .045       0  1173.7     .08       0
Bank Sta=1143.7,1173.7
XS Rating Curve= 0 ,0
Exp/Cntr=0.3,0.1

Type RM Length L Ch R = 1 ,23587.8 ,869,872.7,879.8
XS GIS Cut Line= 3
     1606452.698      382772.858     1607066.836      382252.595
     1607378.627      381923.664
#Sta/Elev= 30
    10.1 1005.06    50.3  998.43   100.6  979.62   231.4  898.18   251.5  887.03
   462.8  806.19   583.5  746.53   603.7  734.93   623.8  721.01   633.8  716.76
   643.9  714.94   779.8  707.94   794.8  707.12   809.8  708.26     815  709.31
   855.2  727.86   885.5  743.51   905.6  747.88   925.7  754.93   935.8  761.45
   976.1  801.49   986.2  808.27   996.2  812.74  1006.3  814.07  1036.5   813.5
    1097  830.37  1137.2   835.6  1187.6  845.77  1207.7  852.32  1258.1  880.62
#Mann= 3 , 0 , 0
       0     .08       0   779.8    .045       0   809.8     .08       0
Bank Sta=779.8,809.8
XS Rating Curve= 0 ,0
Exp/Cntr=0.3,0.1

Type RM Length L Ch R = 1 ,22715.1 ,535.2,538.3,541.1
XS GIS Cut Line= 3
     1606623.125      383326.744     1607262.224      383122.232
     1607778.806      382787.984
#Sta/Elev= 30
      10  999.45    40.1 1000.09    60.1  998.02   150.2  981.19   170.3   975.3
   190.3  966.57   230.4  941.45   240.4  936.49   320.5  903.16   470.7  845.95
   560.9  808.46   610.9  785.53   751.7   716.5   777.1  706.22     782  704.41
   792.1  702.62   802.2  703.52   807.1  704.76   822.3  707.77   923.2  710.12
   933.3  711.03   943.4  713.91   953.5  719.51   983.7  739.37   993.8  744.27
  1003.9  747.53    1014  752.12  1054.3  774.33    1135   817.3  1286.3  888.89
#Mann= 3 , 0 , 0
       0      .1       0   777.1    .045       0   807.1      .1       0
Bank Sta=777.1,807.1
XS Rating Curve= 0 ,0
Exp/Cntr=0.3,0.1

Type RM Length L Ch R = 1 ,22176.8 ,325.7,347.5,369.5
XS GIS Cut Line= 5
     1606691.295      383531.256     1607577.513      383497.171
     1608003.579      383258.574      1608455.21      381792.906
      1608523.38      381622.479
#Sta/Elev= 30
    10.1  950.07   221.7   994.2   332.6   974.7     383  956.26   574.5  864.58
   876.8  760.79   926.7  735.85   986.5  712.11  1006.5  707.63  1101.1  702.92
  1116.1  700.23  1131.1  701.46  1175.9  711.54  1215.7  730.83  1235.7  736.25
  1375.2  735.39  1415.8  748.15  1629.1  834.35  1690.1  848.69    1883  859.87
  1933.8  856.25  2045.5  837.29  2329.9   880.5    2462  873.38  2614.3  854.62
    2655  870.43  2776.8  939.59  2847.9  973.05  2966.8 1018.06  3092.4 1055.29
#Mann= 3 , 0 , 0
       0      .1       0  1101.1    .045       0  1131.1      .1       0
Bank Sta=1101.1,1131.1
XS Rating Curve= 0 ,0
Exp/Cntr=0.3,0.1

Type RM Length L Ch R = 1 ,21829.3 ,625.7,641.5,660.5
XS GIS Cut Line= 4
     1606708.338      383607.948     1607662.726      383599.427
     1608165.485      383727.247     1609682.281      384332.261
#Sta/Elev= 30
    10.2  934.23   243.7  995.27   284.3  996.66   436.6  951.53   619.4  865.91
   720.9  835.06     924  759.21   994.3  740.62  1064.2  714.27  1228.7  700.54
  1243.7  697.94  1258.7  699.59  1283.6  709.95  1323.5  740.49  1403.3  777.63
  1453.2  810.97  1615.2  871.08  1807.9  966.25  1878.9  988.11  1929.6  993.64
  2020.9  972.63    2102  944.69  2193.3  902.52  2233.9  928.53  2467.2  998.91
  2680.2  984.51  2852.6 1033.67  2933.8  1050.1  3014.9 1056.96  3106.2 1052.82
#Mann= 3 , 0 , 0
       0      .1       0  1228.7    .045       0  1258.7      .1       0
Bank Sta=1228.7,1258.7
XS Rating Curve= 0 ,0
Exp/Cntr=0.3,0.1

Type RM Length L Ch R = 1 ,21187.8 ,795.3,800,803
XS GIS Cut Line= 3
     1607164.306      383763.594     1607494.344      384091.249
     1607781.388      384442.012
#Sta/Elev= 30
    10.1  880.08   151.7  812.93     182   799.4   232.5  768.18   313.4  716.77
   323.5  711.76   333.6  709.25   424.6  704.05   450.1  699.15  454.97  697.45
   465.1  698.19   480.1  701.97   495.3  705.84   525.5   707.8   535.6  711.23
   565.8   728.6   575.9  733.21     596  737.56   606.1   740.9   616.1  745.73
   636.3  757.45   686.6  788.58   696.7  794.46   706.8  799.23   767.2  817.54
   807.5  830.76   827.7  838.15   857.9  851.33     878  858.68   918.3  868.18
#Mann= 3 , 0 , 0
    10.1      .1       0   450.1    .045       0   480.1      .1       0
Bank Sta=450.1,480.1
XS Rating Curve= 0 ,0
Exp/Cntr=0.3,0.1

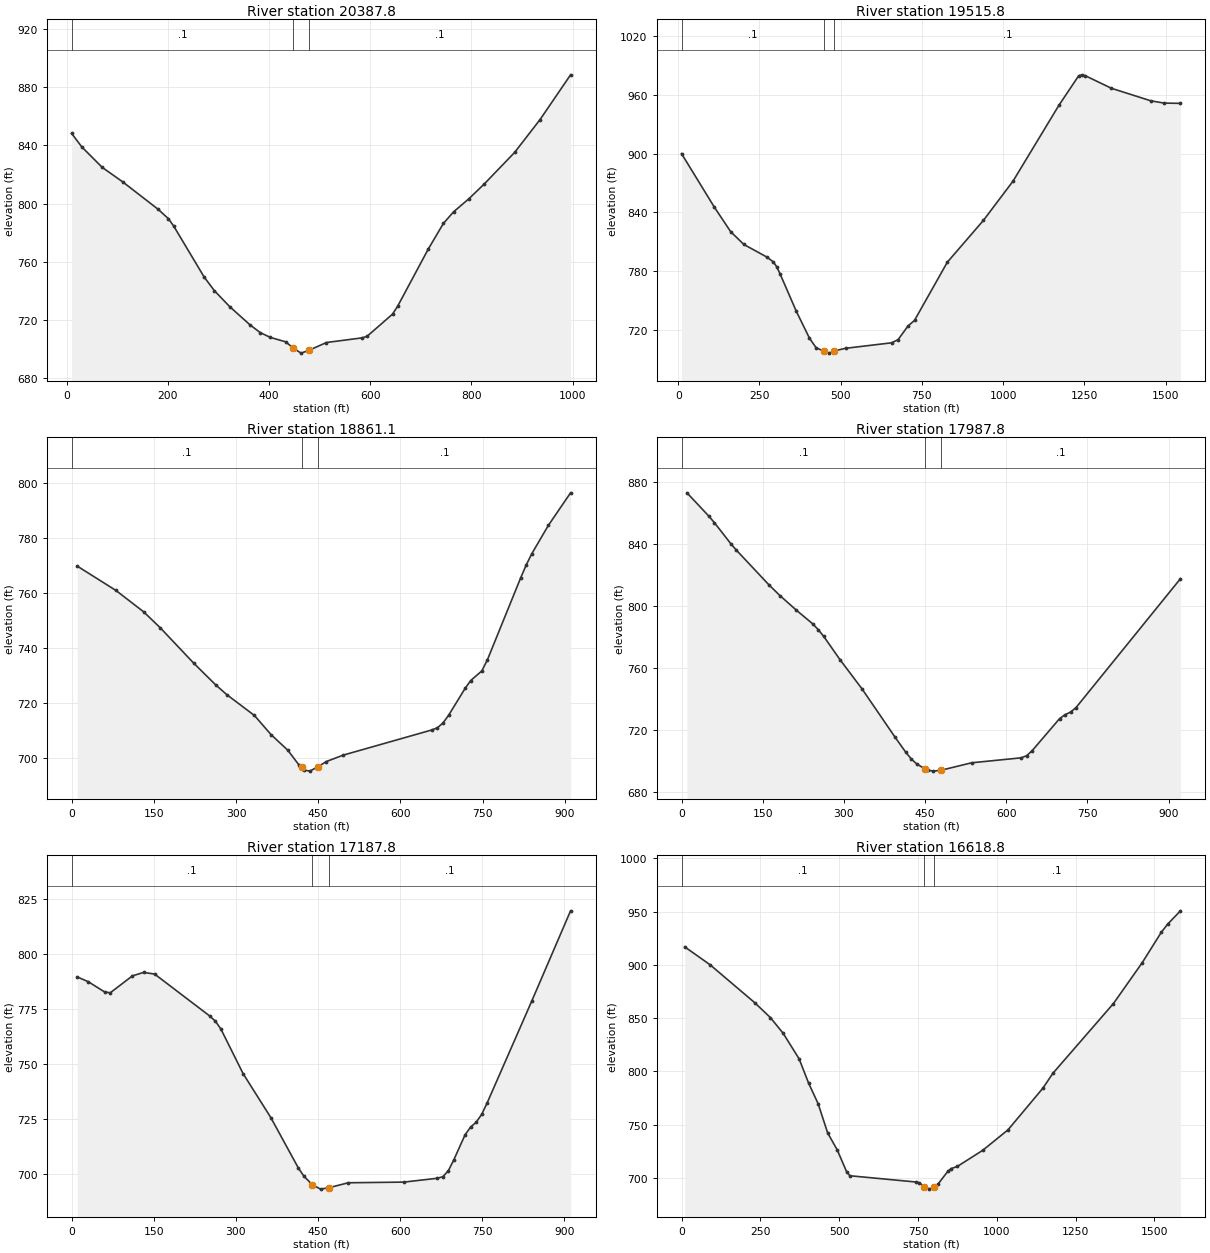
Type RM Length L Ch R = 1 ,20387.8 ,871.5,872,871.1
XS GIS Cut Line= 3
     1606573.667       384145.97     1606847.624      384519.512
     1607142.926      384962.839
#Sta/Elev= 30
    10.1  848.28    30.2  838.97    70.5  824.89   110.8  814.96   181.3  795.95
   201.4  789.52   211.5  784.63   271.9  749.43     292  740.06   322.2  729.09
   362.5  716.49   382.7  711.14   402.8  707.81     433  704.79   448.2  700.43
  463.43     697   478.2  698.81   513.5   704.3   583.8   707.5   593.9  708.58
   644.1  723.83   654.2  729.26   714.5  768.48   744.6  786.26   764.7  794.26
   794.9  803.23   825.1  813.34   885.4  835.17   935.6  857.77   995.9  888.58
#Mann= 3 , 0 , 0
    10.1      .1       0   448.2    .045       0   478.2      .1       0
Bank Sta=448.2,478.2
XS Rating Curve= 0 ,0
Exp/Cntr=0.3,0.1

Type RM Length L Ch R = 1 ,19515.8 ,668.8,654.7,640.6
XS GIS Cut Line= 3
     1605788.035       384195.92     1606231.144      384835.019
     1606725.381      385422.991
#Sta/Elev= 30
    10.1     900   111.1  845.23   161.6  820.04     202  807.05   272.7  794.16
   292.9  789.19     303  784.21   313.1  777.17   363.6  738.54     404  711.09
   424.2  701.49   449.6  697.57  464.62  695.86   479.6  698.03   515.1   700.8
   656.5  706.41   676.7  709.66     707   723.5   727.2  729.36   828.2  788.88
   939.4  831.72  1030.3  871.77  1171.8  949.51  1232.5  979.63  1242.6   980.6
  1252.7  979.72  1333.5   966.8  1454.8  953.99  1495.3  951.69  1545.8   951.4
#Mann= 3 , 0 , 0
    10.1      .1       0   449.6    .045       0   479.6      .1       0
Bank Sta=449.6,479.6
XS Rating Curve= 0 ,0
Exp/Cntr=0.3,0.1

Type RM Length L Ch R = 1 ,18861.1 ,885.4,873.3,864.5
XS GIS Cut Line= 3
     1605203.125       384814.82     1605604.313      385029.259
     1606006.996      385242.179
#Sta/Elev= 30
    10.1  769.78    80.9   760.9   131.4  753.14   161.7  747.34   222.4  734.55
   262.8  726.59   283.1  723.03   333.6  715.44   363.9  708.48   394.2  702.87
   414.5  697.55   419.7  696.54   424.6  695.59   434.7  695.21   449.7  696.84
     465  698.71   495.4  701.02   657.4  710.19   667.5  710.99   677.6  712.71
   687.7  715.46   718.1  725.33   728.2  728.15   748.5  731.65   758.6  735.65
   819.3  765.45   829.4  770.13   839.6  774.24   869.9  784.57   910.4   796.4
#Mann= 3 , 0 , 0
       0      .1       0   419.7    .045       0   449.7      .1       0
Bank Sta=419.7,449.7
XS Rating Curve= 0 ,0
Exp/Cntr=0.3,0.1

Type RM Length L Ch R = 1 ,17987.8 ,805.3,800,791.1
XS GIS Cut Line= 3
     1604867.731       385806.45     1605330.922      385847.351
     1605779.223      385936.311
#Sta/Elev= 30
    10.1  872.76    50.5  857.74    60.7  853.58      91  840.04   101.1  835.94
   161.7  813.45     182  806.55   212.3  797.17   242.6  788.35   252.7  784.63
   262.8   780.3   293.1  765.21   333.6  746.49   394.2  715.61   414.4  705.71
   424.6  701.39   434.7  698.15     450     695   454.9   694.2     465  693.55
     480  694.15   536.1  698.92   627.5  702.11   637.7  703.48   647.8  706.66
   698.6  727.35   708.7  729.88   718.9  731.55   729.1  734.52     922  817.48
#Mann= 3 , 0 , 0
       0      .1       0     450    .045       0     480      .1       0
Bank Sta=450,480
XS Rating Curve= 0 ,0
Exp/Cntr=0.3,0.1

Type RM Length L Ch R = 1 ,17187.8 ,554.9,569,583.4
XS GIS Cut Line= 3
     1604914.745      386682.717     1605367.655      386642.417
     1605822.099      386597.027
#Sta/Elev= 30
    10.1  789.72    30.3  787.54    60.6  782.83    70.7  782.51   111.1  790.19
   131.4  791.74   151.6  791.01   252.6  771.89   262.7  769.59   272.8  765.97
   313.2   745.8   363.8  725.85   414.3  702.86   424.4  699.17   439.7  695.32
   454.7  693.32   469.7  693.95   505.4  696.21   606.9  696.51   667.8  698.25
     678  698.96   688.1  701.65   698.3  706.71   718.6  717.94   728.7  721.48
   738.9  723.68     749  727.25   759.2  732.58   840.4  778.67   911.4  819.72
#Mann= 3 , 0 , 0
       0      .1       0   439.7    .045       0   469.7      .1       0
Bank Sta=439.7,469.7
XS Rating Curve= 0 ,0
Exp/Cntr=0.3,0.1

Type RM Length L Ch R = 1 ,16618.8 ,862.4,876.9,891.4
XS GIS Cut Line= 4
     1604782.518      387033.521     1605285.276      387067.607
     1605779.513      387263.597     1606299.314      387434.024
#Sta/Elev= 30
    10.1   916.9    90.7  900.05   231.8  864.61   282.2  850.43   322.5  835.73
   372.9  811.87   403.1  789.05   433.4  769.66   463.6  742.27   493.8  726.43
     524  705.66     534  702.14   744.7  696.23   754.7  695.47   769.8  691.94
   784.8  689.58   799.8  691.16   814.9  694.82     845  706.42     855  708.81
   875.1  710.91   955.3  725.97  1035.6  745.21    1147  784.58  1177.4  798.08
  1369.9  863.66  1461.1  901.96  1521.8  930.54  1542.1  938.26  1582.6  950.68
#Mann= 3 , 0 , 0
       0      .1       0   769.8    .045       0   799.8      .1       0
Bank Sta=769.8,799.8
XS Rating Curve= 0 ,0
Exp/Cntr=0.3,0.1

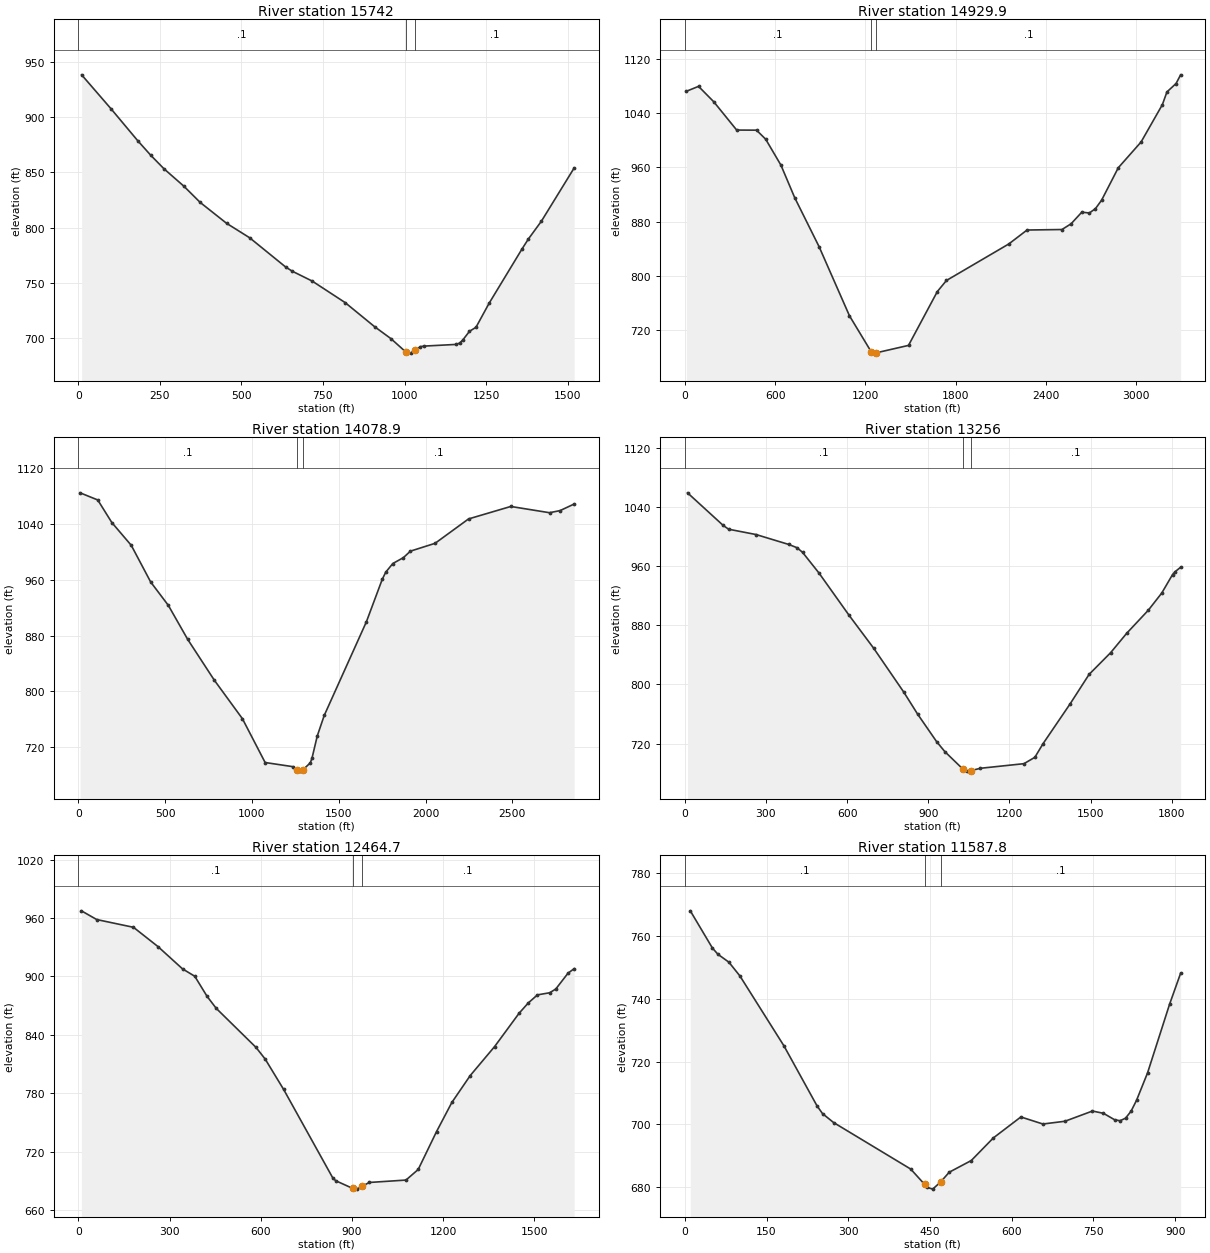
Type RM Length L Ch R = 1 ,15742   ,823.4,812.1,800.8
XS GIS Cut Line= 3
     1604220.111      386956.829     1604791.039      387570.365
     1605242.017      388082.014
#Sta/Elev= 30
    10.1  938.37     101  907.34   181.8   878.8   222.1  865.49   262.5  853.28
   323.1  837.62   373.6  822.79   454.4   803.9   525.1   790.8   636.1  764.18
   656.3  760.43   716.9  751.57   817.9  732.08   908.3  710.24   958.4   699.4
  1003.6  687.45  1018.6  686.29  1033.6  689.17  1048.7  692.12  1058.7  692.64
    1159  694.19  1169.1  695.45  1179.1  698.35  1199.2  706.05  1219.2  709.72
  1259.3  731.44  1359.6  780.32  1379.7  789.63  1419.8  805.85  1520.1  854.01
#Mann= 3 , 0 , 0
       0      .1       0  1003.6    .045       0  1033.6      .1       0
Bank Sta=1003.6,1033.6
XS Rating Curve= 0 ,0
Exp/Cntr=0.3,0.1

Type RM Length L Ch R = 1 ,14929.9 ,817.1,850.9,884.8
XS GIS Cut Line= 4
     1603325.371      387672.621     1604177.504        388183.9
     1604722.869      388465.104     1606410.091      388499.189
#Sta/Elev= 30
    10.1 1072.28    91.3 1079.58   192.7 1056.78   344.8 1015.08   476.6 1014.91
   537.4 1001.61   638.8   963.3   730.1  915.39   892.3  842.96  1094.3  740.88
  1240.3   687.2  1255.3  685.78  1270.3  686.15  1486.6  697.19  1678.1  776.64
  1738.7  793.01    2153  846.92  2274.3  867.51  2506.7  868.26  2567.3  876.79
  2638.1  893.84  2688.6  892.67    2729   899.1  2769.4  911.41  2880.6  959.41
  3032.2   997.5  3173.6 1052.59    3204 1071.36  3264.6 1083.79  3294.9 1096.61
#Mann= 3 , 0 , 0
       0      .1       0  1240.3    .045       0  1270.3      .1       0
Bank Sta=1240.3,1270.3
XS Rating Curve= 0 ,0
Exp/Cntr=0.3,0.1

Type RM Length L Ch R = 1 ,14078.9 ,833.1,822.9,812.7
XS GIS Cut Line= 4
     1603427.627      387894.175     1603990.035      388703.701
     1603972.992      389163.853     1603734.395      390552.829
#Sta/Elev= 30
    10.2 1084.92   111.8 1074.67   193.1 1042.18   304.9 1009.48   416.6  956.87
   518.3  923.28     630  874.36   782.5  816.04   945.1  760.45  1075.8  697.57
    1236  691.59    1261  687.04    1276   685.2    1291  686.52  1336.1  697.11
  1346.1  704.16  1376.1  735.76  1416.2  765.21  1659.1  899.77  1750.4  960.77
  1770.6  971.01  1811.2  983.41    1872  991.82  1912.6 1001.16  2054.5  1012.4
  2247.2 1047.43  2490.5 1065.33  2713.6 1056.35  2774.4 1059.39  2855.5 1068.85
#Mann= 3 , 0 , 0
       0      .1       0    1261    .045       0    1291      .1       0
Bank Sta=1261,1291
XS Rating Curve= 0 ,0
Exp/Cntr=0.3,0.1

Type RM Length L Ch R = 1 ,13256   ,794.7,791.3,787.9
XS GIS Cut Line= 4
     1603103.817       387860.09     1603112.338      388720.744
     1603274.243      389240.545     1603521.362      389589.919
#Sta/Elev= 30
    10.1 1059.17   141.8 1015.13     162 1009.95   263.3 1002.77   384.8   989.3
   415.2  984.89   435.4  978.67   496.2  950.65   607.6   893.4   698.7   848.8
   810.1  789.36   860.7  759.91   931.3  722.51   961.5  709.13  1027.2  685.88
  1042.2  682.79  1057.2  683.39  1092.6  686.63  1253.9  692.86  1294.2  701.49
  1324.5  719.93    1425     774  1494.7  813.61  1574.3  842.95    1634  869.32
  1713.6  900.38  1763.4  923.66  1803.2  948.59  1813.2  952.68  1833.1  958.51
#Mann= 3 , 0 , 0
       0      .1       0  1027.2    .045       0  1057.2      .1       0
Bank Sta=1027.2,1057.2
XS Rating Curve= 0 ,0
Exp/Cntr=0.3,0.1

Type RM Length L Ch R = 1 ,12464.7 ,863.5,876.9,890.6
XS GIS Cut Line= 4
     1602081.258      388490.668     1602430.632      389138.289
     1602631.942      389577.032     1602745.921      389973.379
#Sta/Elev= 30
    10.1  967.33    60.5  958.37   181.4  950.41   262.1  930.57   342.7  907.72
     383  900.13   423.4  879.54   453.6  867.17   584.6  827.01   614.9  814.95
   675.4  783.85   836.4  693.33   846.5  690.15   901.9  682.31   916.9  681.49
   931.9  684.19   957.1  688.33  1077.8   690.8    1118  701.67  1178.3  740.58
  1228.6  770.47    1289  798.08  1369.5  827.98  1449.9  862.16  1480.1  872.72
  1510.3  881.01  1550.5  883.18  1570.6  887.04  1610.9  903.33    1631  907.91
#Mann= 3 , 0 , 0
       0      .1       0   901.9    .045       0   931.9      .1       0
Bank Sta=901.9,931.9
XS Rating Curve= 0 ,0
Exp/Cntr=0.3,0.1

Type RM Length L Ch R = 1 ,11587.8 ,708,704.6,701
XS GIS Cut Line= 3
      1601713.23      388993.384     1601697.665      389448.116
      1601680.18      389902.785
#Sta/Elev= 30
    10.1  768.07    50.6  756.23    60.7  754.23    80.9   751.7   101.1  747.32
     182  725.01   242.7  705.88   252.8  703.41     273  700.58   414.6  685.74
     440  680.88   444.9  679.88     455  679.34     470  681.71   485.3  684.73
   525.8  688.46   566.2  695.65   616.8  702.35   657.2   700.1   697.7  700.98
   748.2  704.24   768.4  703.51   788.7  701.47   798.8  701.14   808.9  701.96
     819  704.17   829.1  707.66   849.3   716.4   889.8  738.33     910  748.18
#Mann= 3 , 0 , 0
       0      .1       0     440    .045       0     470      .1       0
Bank Sta=440,470
XS Rating Curve= 0 ,0
Exp/Cntr=0.3,0.1

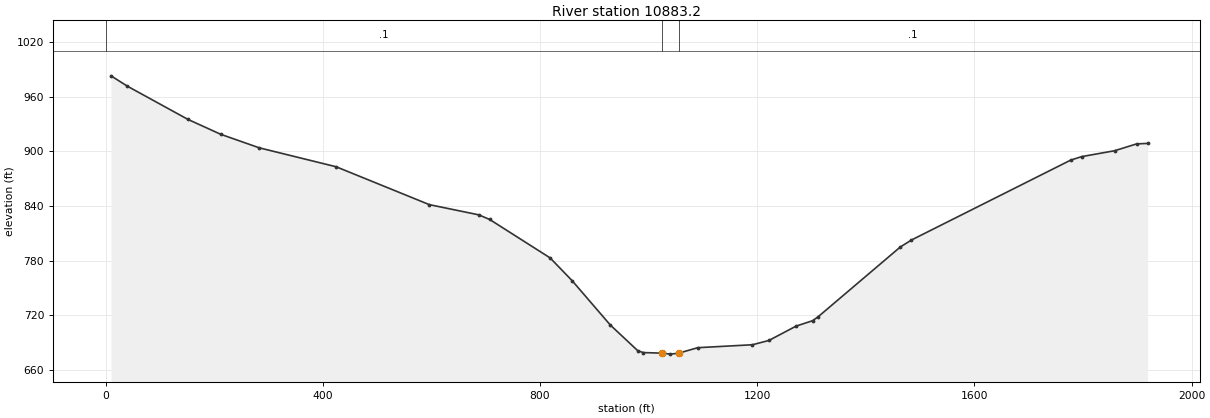
Type RM Length L Ch R = 1 ,10883.2 ,909.8,895.4,883.1
XS GIS Cut Line= 4
     1601246.168      388499.189     1600990.528      389308.715
     1601034.751      389789.759     1601280.253      390322.753
#Sta/Elev= 30
    10.1  982.69    40.4  971.28   151.6  934.95   212.2  918.55     283  903.74
   424.5  882.98   596.3   841.4   687.2  830.23   707.4  825.13   818.6  783.01
     859  758.13   929.4  709.43   979.8  681.34   989.8  679.19  1025.1  678.52
  1040.1  677.46  1055.1  678.48  1090.5  684.52  1191.1  687.74  1221.3  692.41
  1271.6   708.2  1301.8   714.1  1311.9  718.32  1463.5  794.99  1483.8  802.57
  1777.2  890.26  1797.4  894.09  1858.1  900.54  1898.6  908.05  1918.8  908.55
#Mann= 3 , 0 , 0
       0      .1       0  1025.1    .045       0  1055.1      .1       0
Bank Sta=1025.1,1055.1
XS Rating Curve= 0 ,0
Exp/Cntr=0.3,0.1