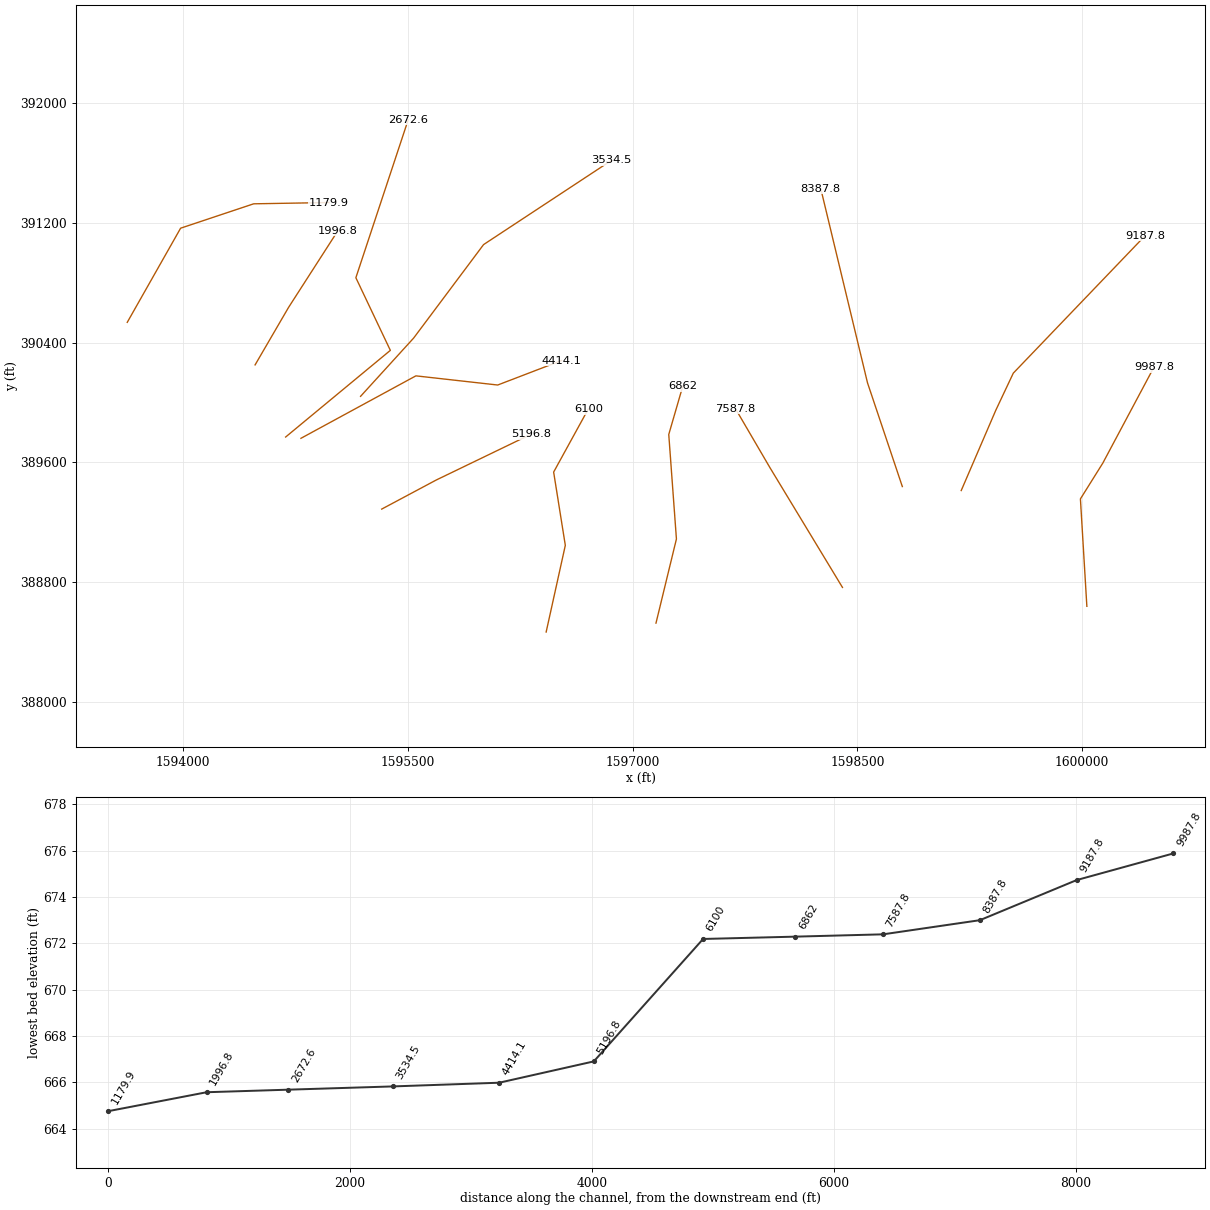
HEC-RAS study KIAHCR.prj: KIAHCR

--- KIAHCR.g01 (geometry) --- (continued)

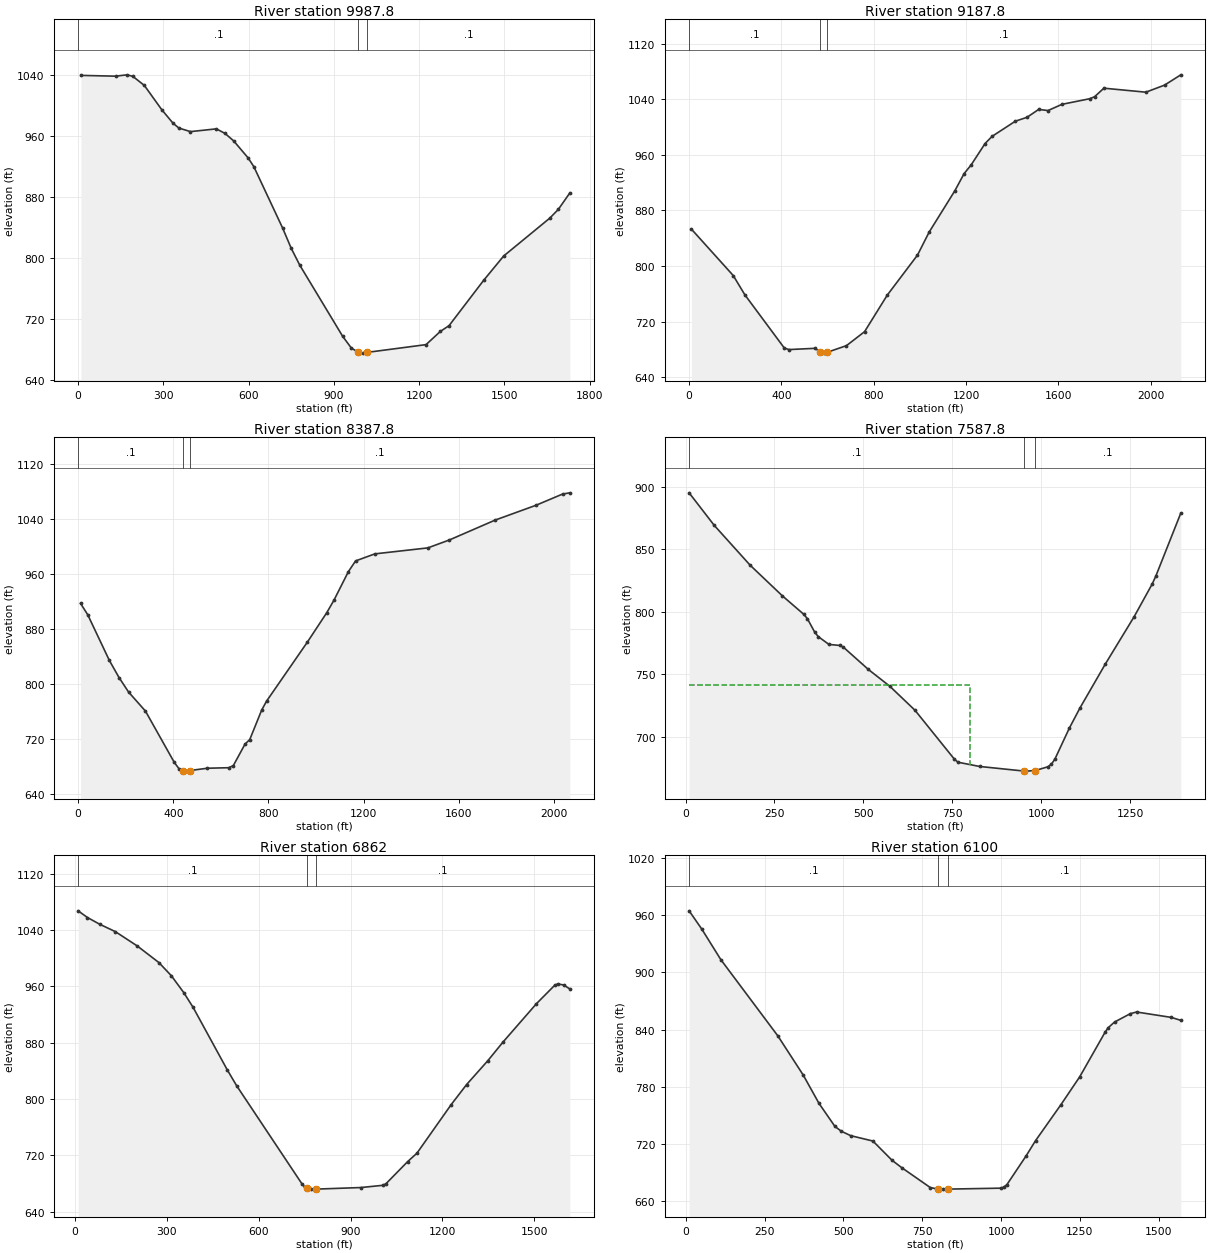
Type RM Length L Ch R = 1 ,9987.8  ,795.4,800,801.5
XS GIS Cut Line= 4
     1600030.789      388636.937     1599987.816      389355.214
     1600137.091       389594.32     1600479.248       390237.54
#Sta/Elev= 30
    10.1 1040.01   131.8 1038.98   172.3 1040.75   192.6 1038.73   233.1 1026.79
   293.9   995.2   334.4  977.09   354.7  970.94   395.3   966.3   486.5  969.91
   516.9  963.91   547.3  954.12   597.9  931.92   618.2  920.38   719.6  839.79
   749.8  813.25     780  791.09     931  697.78   961.2   682.6   986.4  676.77
  1001.4  675.88  1016.4  676.83  1224.1  687.02  1274.6   704.4    1305  711.88
  1426.4  771.12  1497.3  803.24  1659.2  852.77  1689.5  864.33    1730  885.88
#Mann= 3 , 0 , 0
       0      .1       0   986.4    .045       0  1016.4      .1       0
Bank Sta=986.4,1016.4
XS Rating Curve= 0 ,0
Exp/Cntr=0.3,0.1

Type RM Length L Ch R = 1 ,9187.8  ,778,800,823
XS GIS Cut Line= 4
     1599192.528      389410.971     1599422.945      389947.428
     1599539.867      390195.891     1600419.599      391115.237
#Sta/Elev= 30
    10.1  853.09   191.3  786.32   241.6   758.6   412.7  681.97   432.9  679.84
   543.6  681.62   568.8   676.9   583.8  674.73   598.8     676   681.9  685.49
   760.4  705.63   858.4  758.05   989.7  815.79  1040.2   848.9  1151.3   908.2
  1191.7  933.03    1222  945.44  1282.6  976.33  1312.9  986.61  1413.9 1008.45
  1464.4 1014.05  1514.9 1025.41  1555.3 1023.76  1615.9 1032.72    1737 1040.83
  1757.2 1043.69  1797.6 1055.93  1979.4 1050.19  2060.2 1060.33  2130.9 1075.16
#Mann= 3 , 0 , 0
       0      .1       0   568.8    .045       0   598.8      .1       0
Bank Sta=568.8,598.8
XS Rating Curve= 0 ,0
Exp/Cntr=0.3,0.1

Type RM Length L Ch R = 1 ,8387.8  ,793.4,800,806.1
XS GIS Cut Line= 4
     1598799.539      389437.757     1598654.997      389869.188
     1598567.174      390131.324     1598255.182      391430.526
#Sta/Elev= 30
    10.1  917.23    40.4  900.67   131.4  834.09   171.9   809.3   212.3  788.04
   283.1  760.41   404.4  685.68   424.7  676.27     440  673.65     455     673
     470  673.88   543.9  677.22   632.7  677.97   652.5  680.99   701.8  712.35
   721.6  718.89   771.9  761.92   792.2   774.8   964.3     861  1045.2  903.47
  1075.6  921.73  1136.3  963.34  1166.7  979.02  1247.7  989.28  1470.4  997.97
  1561.5 1009.59  1753.8 1038.49  1925.9 1060.11  2037.2 1076.38  2067.6 1078.15
#Mann= 3 , 0 , 0
       0      .1       0     440    .045       0     470      .1       0
Bank Sta=440,470
XS Rating Curve= 0 ,0
Exp/Cntr=0.3,0.1

Type RM Length L Ch R = 1 ,7587.8  ,740.1,725.8,712.1
XS GIS Cut Line= 3
     1598400.045       388763.35     1597915.391      389565.546
     1597686.167      389958.586
#Sta/Elev= 30
    10.1  895.25    80.6  869.23   181.4  837.35   272.1  812.78   332.6  797.92
   342.6  794.43   362.8  783.83   372.9  780.14   403.1  773.85   433.3  773.05
   443.4  771.72     514  753.79   574.4   740.3     645  721.12   755.8  681.92
   765.9  679.51   826.4  676.14   952.6   672.4   957.5  672.39   982.6  672.84
  1018.1  675.83  1028.2  677.83  1038.3  682.06  1078.8  706.81  1109.1  723.19
  1179.9  758.12  1260.8  795.98  1311.3  822.02  1321.5  828.26  1392.2  879.08
#Mann= 3 , 0 , 0
    10.1      .1       0   952.6    .045       0   982.6      .1       0
#XS Ineff= 2 , 0
          800.71  741.43
Permanent Ineff=
       F       F
Bank Sta=952.6,982.6
XS Rating Curve= 0 ,0
Exp/Cntr=0.3,0.1

Type RM Length L Ch R = 1 ,6862    ,759.4,762,764.5
XS GIS Cut Line= 4
     1597155.931      388524.753     1597292.272      389087.161
     1597241.144       389785.91     1597334.879       390109.72
#Sta/Elev= 30
    10.2 1067.08    40.6 1057.61    81.2 1047.95     132 1037.52   203.1 1017.33
   274.1  993.68   314.7  975.02   355.3  951.06   385.8  930.13   497.5  841.37
   527.9  819.04   741.2  679.86   751.3  674.82   756.6  673.62   771.6  672.29
   786.6   672.3   934.1  674.55  1005.2  677.68  1015.3  679.71  1086.4  711.24
  1116.9  723.24  1228.5  791.99  1279.3   820.7  1348.7  854.57  1398.3  881.01
  1507.4  935.38  1566.8  961.38  1576.8  963.39  1596.6  961.85  1616.4  956.25
#Mann= 3 , 0 , 0
    10.2      .1       0   756.6    .045       0   786.6      .1       0
Bank Sta=756.6,786.6
XS Rating Curve= 0 ,0
Exp/Cntr=0.3,0.1

Type RM Length L Ch R = 1 ,6100    ,939.9,903.2,865
XS GIS Cut Line= 4
     1596423.097      388465.104     1596550.917      389044.554
     1596473.026      389534.565     1596704.301      389956.336
#Sta/Elev= 30
    10.1   964.8    50.3  945.59   110.6  913.54   291.7  833.29   372.1  792.19
   422.4  762.27   472.7  738.18   492.8  733.09     523   728.4   593.4  722.74
   654.1  702.52   684.5  694.84   775.6  673.81   801.1  672.23   816.1  672.19
   831.1   672.2   998.4   673.2  1008.5  674.18  1018.7  676.95  1079.4  707.05
  1109.6  723.19  1189.8  760.85  1249.9  790.39  1330.1  837.09  1340.1   841.9
  1360.1  847.85  1410.2  856.66  1430.3  858.42  1540.5  852.73  1570.6  849.64
#Mann= 3 , 0 , 0
    10.1      .1       0   801.1    .045       0   831.1      .1       0
Bank Sta=801.1,831.1
XS Rating Curve= 0 ,0
Exp/Cntr=0.3,0.1

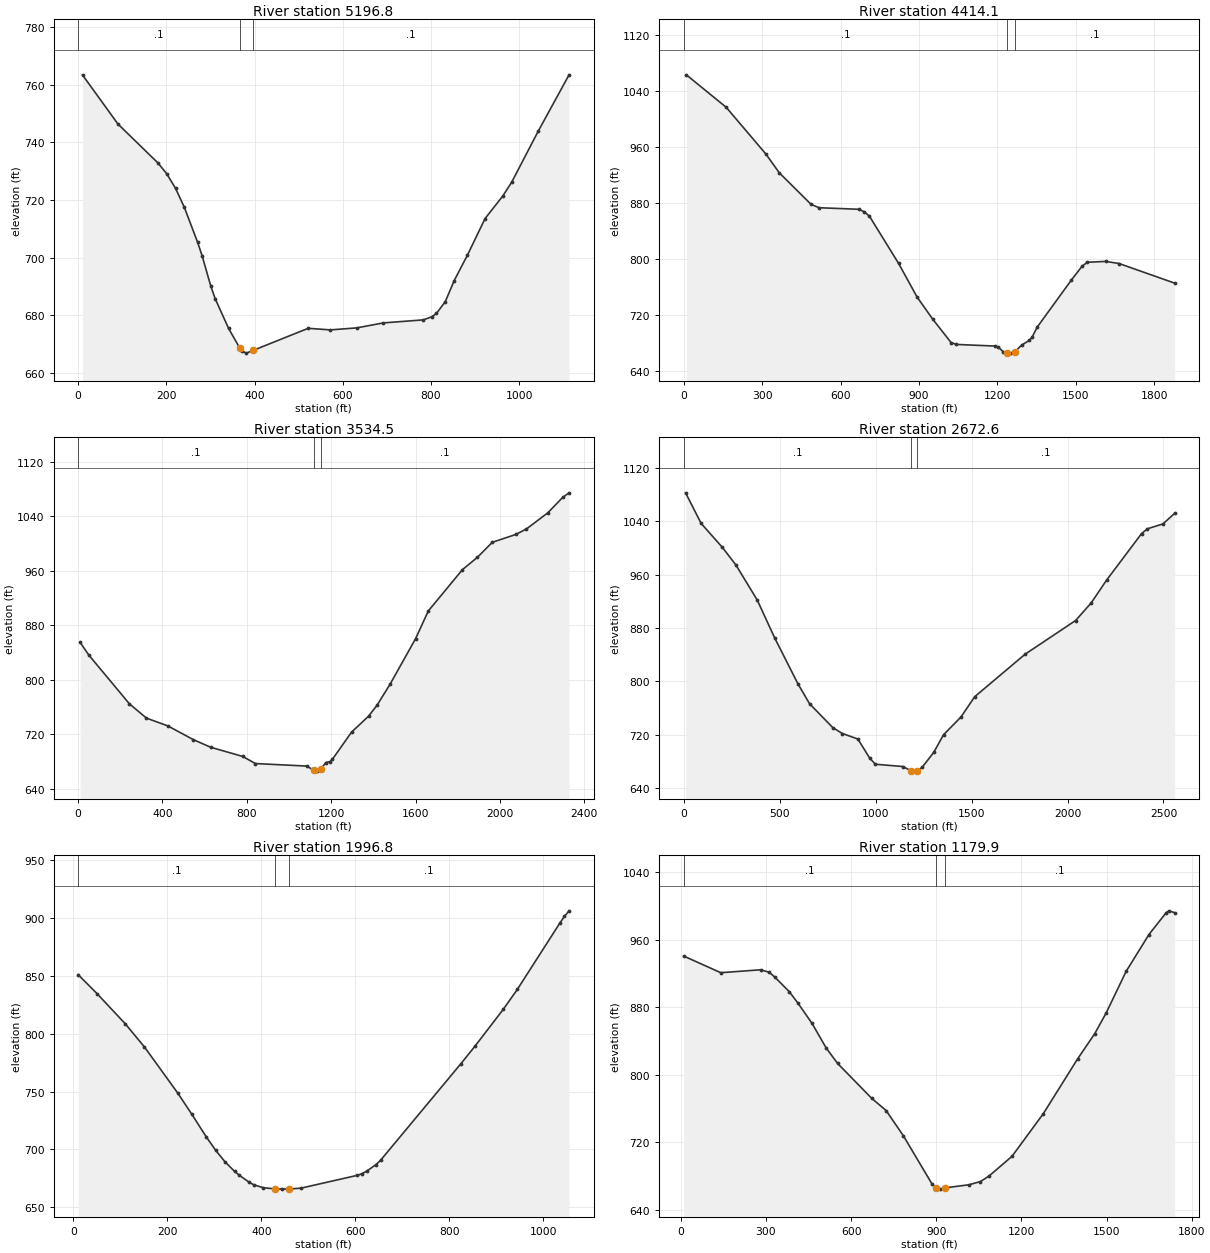
Type RM Length L Ch R = 1 ,5196.8  ,801.2,782.7,765.8
XS GIS Cut Line= 3
      1595325.87      389286.997     1595688.705      389480.937
     1596320.072      389786.442
#Sta/Elev= 30
      10  763.41    90.3  746.39   180.6  732.94   200.7  729.18   220.8   724.1
   240.8  717.49   270.9  705.36     281  700.74     301  690.03   311.1  685.65
   341.2  675.46   366.3   668.7   371.3   667.6   381.3  666.91   396.3  667.83
   521.6  675.52   571.7  674.97   631.9  675.67     692   677.4   782.2  678.44
   802.2  679.54   812.2  680.68   832.3  684.77   852.3  692.02   882.4  700.88
   922.4  713.59   962.5  721.39   982.6  726.16  1042.7  743.84  1112.8  763.45
#Mann= 3 , 0 , 0
       0      .1       0   366.3    .045       0   396.3      .1       0
Bank Sta=366.3,396.3
XS Rating Curve= 0 ,0
Exp/Cntr=0.3,0.1

Type RM Length L Ch R = 1 ,4414.1  ,848.4,879.6,910.8
XS GIS Cut Line= 4
     1594787.002      389760.346     1595553.922      390177.891
     1596099.783      390116.576     1596525.353      390280.147
#Sta/Elev= 30
    10.2 1062.97   162.5 1016.75   314.8  949.87   365.5  923.33   487.4  878.23
   517.8   873.4   670.1  871.18   690.5  867.69   710.8  861.26   822.4  793.89
   893.2  745.84   953.1  714.32    1023  681.11    1043  678.41  1192.8  676.05
  1202.8  674.84  1222.8  667.87  1237.7  666.15  1252.7  665.99  1267.7  668.02
  1292.7  677.41  1322.6  684.14  1332.6  688.47  1352.6  703.09  1483.3  770.24
  1523.8  789.75  1544.1   795.6    1615   796.8  1665.7  793.82  1878.4  765.84
#Mann= 3 , 0 , 0
       0      .1       0  1237.7    .045       0  1267.7      .1       0
Bank Sta=1237.7,1267.7
XS Rating Curve= 0 ,0
Exp/Cntr=0.3,0.1

Type RM Length L Ch R = 1 ,3534.5  ,831.4,861.9,892.4
XS GIS Cut Line= 4
     1595184.776      390040.968     1595539.095      390430.741
     1596005.552      391055.587     1596857.685      391617.995
#Sta/Elev= 30
    10.1  854.76    50.6  836.33   243.1  764.72   324.2  743.65   425.5  732.22
     547  711.98     628  700.94   779.9  687.45   840.7  676.95  1083.7  673.26
  1119.4   666.8  1134.3  665.83  1149.4  668.44  1174.9  678.47  1195.1  679.91
  1205.2  683.01  1296.4  723.08  1377.3   746.6  1417.7  762.83  1478.4  793.13
  1599.7  860.17  1660.3  901.03  1822.1   961.7  1892.8  979.69  1963.6 1001.83
  2074.8  1013.3  2125.3 1021.39  2226.4 1045.04  2297.2  1067.7  2327.5 1074.47
#Mann= 3 , 0 , 0
       0      .1       0  1119.4    .045       0  1149.4      .1       0
Bank Sta=1119.4,1149.4
XS Rating Curve= 0 ,0
Exp/Cntr=0.3,0.1

Type RM Length L Ch R = 1 ,2672.6  ,703.3,675.8,646.9
XS GIS Cut Line= 4
     1594684.746      389768.867     1595383.495      390348.317
     1595153.419      390834.033     1595502.794      391890.677
#Sta/Elev= 30
    10.1 1082.66    90.8 1036.87   201.7 1000.91   272.3   974.5   383.3  922.02
     474  865.38   595.1  796.64   655.6  766.82   776.6  730.94   827.1  722.06
   907.8  713.77   968.6  685.41     999  675.99    1141  672.62  1186.8  666.01
  1201.8  665.69  1216.8  666.05  1242.4  671.37  1303.2  693.85  1353.9   720.2
  1445.2   746.9    1516   777.1  1779.1  840.88  2042.1  891.37  2123.1  917.63
    2204  952.06  2386.1  1021.7  2416.5 1028.81  2497.4 1036.12  2558.1 1051.94
#Mann= 3 , 0 , 0
       0      .1       0  1186.8    .045       0  1216.8      .1       0
Bank Sta=1186.8,1216.8
XS Rating Curve= 0 ,0
Exp/Cntr=0.3,0.1

Type RM Length L Ch R = 1 ,1996.8  ,838.6,816.9,796.4
XS GIS Cut Line= 3
     1594481.017      390251.147     1594704.123      390635.181
     1595034.121      391149.322
#Sta/Elev= 30
    10.1   851.1    50.5  834.61     111  808.33   151.4  788.48   222.1  748.72
   252.4   730.2   282.6  710.97   302.8  699.22     323  689.09   343.2  680.94
   353.3  677.59   373.5  671.73   383.6   669.4   403.8  666.85   429.1  665.75
  443.58  665.58   459.1   665.7   484.2   666.4   604.4  677.51   614.4  678.94
   624.4  681.12   644.4  686.84   654.5  690.83   824.7  773.94   854.8  789.16
   914.9  820.97   944.9  838.22    1035  895.31  1045.1  901.36  1055.1  906.24
#Mann= 3 , 0 , 0
    10.1      .1       0   429.1    .045       0   459.1      .1       0
Bank Sta=429.1,459.1
XS Rating Curve= 0 ,0
Exp/Cntr=0.3,0.1

Type RM Length L Ch R = 1 ,1179.9  ,1208,1179.9,1151.8
XS GIS Cut Line= 4
     1593628.102      390535.786     1593984.197      391165.325
     1594471.713       391328.27     1594974.472      391336.791
#Sta/Elev= 30
      10   940.8   140.6  921.08   281.3  924.53   311.4  921.61   331.5  915.75
   381.7  898.76   411.9  885.44   462.1  861.17   512.3  831.84   552.5   813.6
     673  772.18   723.3  757.87   783.7  728.22   884.5  671.21   899.8  666.25
  914.78  664.76   929.8  666.19  1015.6  669.94  1055.9  673.77  1086.1   680.3
  1166.7  703.51  1277.5  754.19  1398.2  819.03  1458.5  848.87  1498.8  873.39
  1569.2  922.69  1649.6  966.31    1710  992.06    1720  994.35  1740.1  992.19
#Mann= 3 , 0 , 0
      10      .1       0   899.8    .045       0   929.8      .1       0
Bank Sta=899.8,929.8
XS Rating Curve= 0 ,0
Exp/Cntr=0.3,0.1

Chan Stop Cuts=-1
Use User Specified Reach Order=0